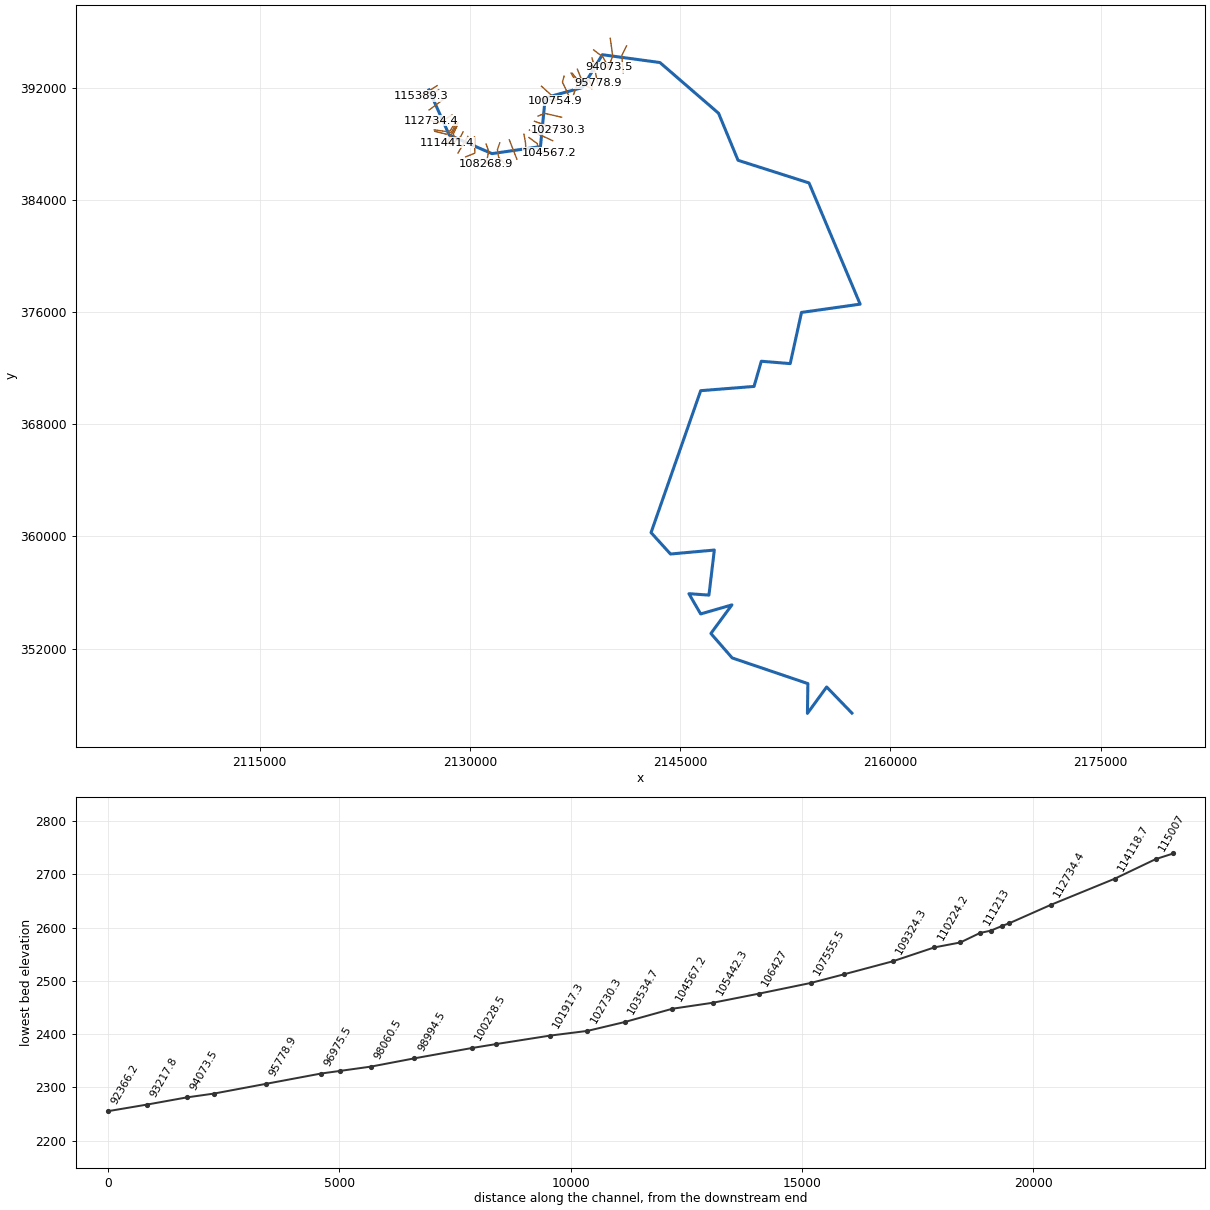
--- SpringCk.prj (project) ---

Proj Title=SpringCk
Current Plan=p01
Geom File=g01
Flow File=f01
Plan File=p01
DSS Export Rating Curves=0
DSS Export Rating Curve Sorted=0
DSS Export Volume Flow Curves=0
DXF OffsetX=0
DXF OffsetY=0
DXF ScaleX=0
DXF ScaleY=0

--- SpringCk.p01 (plan) ---

Plan Title=Floodplain
Program Version=4.00
Geom File=g01
Flow File=f01
K Sum by GR=0
Std Step Tol=0.01
Critical Tol=0.01
Num of Std Step Trials=20
Max Error Tol=0.3
Flow Tol Ratio=0.001
Split Flow NTrial=30
Split Flow Tol=0.02
Split Flow Ratio=0.02
Log Output Level=0
Friction Slope Method=1
Unsteady Friction Slope Method=2
Unsteady Bridges Friction Slope Method=1
Global Log Level=0
CheckData=False
Run HTab=0
Run UNet=0
Run PostProcess=0
UNET Theta=0
UNET Theta Warmup=0
UNET ZTol=0
UNET ZSATol=0
UNET MxIter=0
UNET MaxInSteps=0
UNET DtIC=0
UNET DtMin=0
UNET MaxCRTS=0
UNET WFStab=0
UNET SFStab=0
UNET WFX=0
UNET SFX=0
UNET DSS MLevel=0
UNET DZMax Abort=0
UNET Convert EG Bridges=0
UNET Use Existing IB Tables=0
UNET Froude Limit=0
UNET Froude Power=0
Write IC File=0
Echo Input=False
Echo Output=False
Write Detailed=0

--- SpringCk.f01 (steady flow) ---

Flow Title=NFF Regression Equation
Program Version=4.00
Number of Profiles=1
Profile Names=P100yr
River Rch & RM=SpringCk,Main      ,115389.3
523.3031
River Rch & RM=SpringCk,Main      ,114118.7
556.0473
River Rch & RM=SpringCk,Main      ,111844.5
612.2292
River Rch & RM=SpringCk,Main      ,111441.4
836.7404
River Rch & RM=SpringCk,Main      ,109324.3
878.6620
River Rch & RM=SpringCk,Main      ,108268.9
1029.545
River Rch & RM=SpringCk,Main      ,107555.5
1074.575
River Rch & RM=SpringCk,Main      ,106427
1198.597
River Rch & RM=SpringCk,Main      ,104567.2
1232.009
River Rch & RM=SpringCk,Main      ,103534.7
1569.143
River Rch & RM=SpringCk,Main      ,98994.5
1739.287
River Rch & RM=SpringCk,Main      ,95778.9
1911.329
River Rch & RM=SpringCk,Main      ,92366.2
2117.470
River Rch & RM=SpringCk,Main      ,90899.3
2829.833
River Rch & RM=SpringCk,Main      ,84416.8
3113.077
River Rch & RM=SpringCk,Main      ,83536.3
3513.547
River Rch & RM=SpringCk,Main      ,74666.6
3732.229
River Rch & RM=SpringCk,Main      ,73714.8
5087.667
River Rch & RM=SpringCk,Main      ,72950.2
5104.011
River Rch & RM=SpringCk,Main      ,72242.9
8748.166
River Rch & RM=SpringCk,Main      ,64246
9386.010
River Rch & RM=SpringCk,Main      ,46067.3
10399.84
River Rch & RM=SpringCk,Main      ,13439.4
11545.81
River Rch & RM=SpringCk,Main      ,1337.8
12816.24
Boundary for River Rch & Prof#=SpringCk,Main      ,1
Up Type=0
Dn Type=3
Dn Slope=0.001144

--- SpringCk.g01 (geometry) ---

Geom Title=USGS 10m DEM
Program Version=4.00

River Reach=SpringCk        ,Main
Reach XY= 30
     2127081.441      391852.771     2128526.507      388627.694
     2131574.497       387304.16      2135032.83      387802.424
     2135373.222      391285.701     2138024.481      392018.325
     2139448.581      394360.669     2143555.399      393802.424
     2147738.319      390184.675     2149128.316      386828.466
     2154190.816      385213.882     2157839.107      376565.037
     2153655.447      375976.841     2152850.796      372325.301
     2150788.039      372493.396     2150268.941      370696.521
     2146463.386      370394.438     2142922.876      360269.727
      2144309.45      358741.949     2147436.765      359024.357
     2147052.506      355811.394     2145624.265      355910.931
     2146460.492      354467.354     2148689.659      355111.452
     2147191.395      353074.559     2148708.756      351329.768
     2154109.798       349498.17     2154078.533      347373.842
     2155450.061      349255.786     2157248.672      347396.412

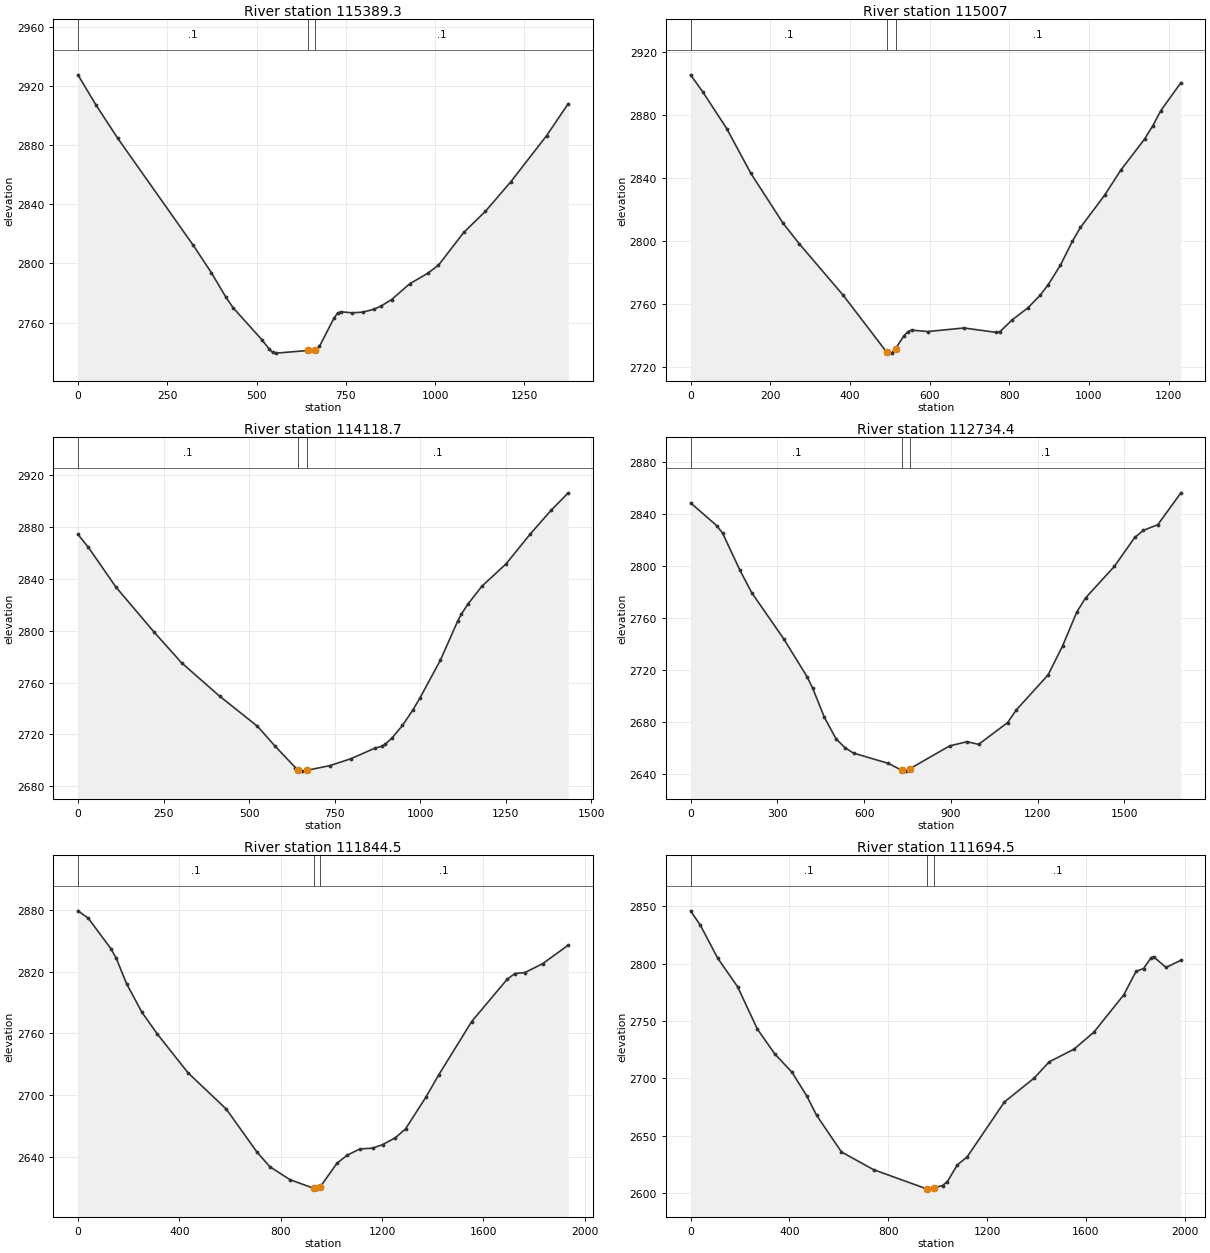
Type RM Length L Ch R = 1 ,115389.3,382.7,382.3,382
XS GIS Cut Line= 2
     2127662.144      392155.594     2126506.388      391415.189
#Sta/Elev= 30
       0 2927.56    50.5 2907.17     111 2884.81     323 2812.21   373.4 2793.81
   413.8 2777.34     434 2770.16   514.7 2748.44   534.9 2742.27     545 2739.77
   555.1 2739.34   643.8 2741.12  664.71 2741.42   676.2 2743.94   716.6 2762.93
   726.7 2766.42   736.8 2767.32     767 2766.59   797.3 2767.05   827.6 2768.95
   847.8 2771.07     878 2775.56   928.5 2786.19     979 2793.31  1009.2 2798.77
  1079.9 2820.93  1140.4 2835.17  1211.1 2855.05    1312 2886.43  1372.6 2908.07
#Mann= 3 , 0 , 0
       0      .1       0   643.8    .045       0  664.71      .1       0
Bank Sta=643.8,664.71
XS Rating Curve= 0 ,0
Exp/Cntr=0.3,0.1

Type RM Length L Ch R = 1 ,115007  ,886.9,888.3,888
XS GIS Cut Line= 2
     2127774.769      391856.271     2126747.627      391177.918
#Sta/Elev= 30
       0 2905.24    30.3 2894.56    90.8 2871.12   151.3 2842.76   232.1 2811.12
   272.4 2798.17   383.4 2765.32   491.9 2729.41   504.5 2728.66   514.6 2731.47
   534.8 2739.36   544.8 2742.12   554.9 2743.29   595.3 2742.35   686.1 2744.62
   766.8 2741.84   776.9 2742.33   807.2  2749.7   847.5 2757.54   877.8 2765.46
     898 2772.13   928.2 2784.38   958.5 2799.65   978.7 2808.38  1039.2 2828.79
  1079.6 2844.64  1140.1 2864.64  1160.3 2872.91  1180.5 2882.53  1230.9 2900.27
#Mann= 3 , 0 , 0
       0      .1       0   491.9    .045       0   514.6      .1       0
Bank Sta=491.9,514.6
XS Rating Curve= 0 ,0
Exp/Cntr=0.3,0.1

Type RM Length L Ch R = 1 ,114118.7,1397.8,1384.3,1384.7
XS GIS Cut Line= 2
     2128238.597      391271.399     2127088.926      390416.889
#Sta/Elev= 30
       0 2874.21    30.3 2864.34     111 2833.61   221.9 2799.12   302.6  2775.3
   413.6 2749.61   524.6 2726.32     575 2711.28   635.5 2694.43   644.3 2692.74
   655.7 2691.75   669.7  2692.4   736.4 2696.03   796.9 2701.25   867.5 2709.46
   887.7 2710.95   897.8 2712.49     918  2717.4   948.2 2726.97   978.5  2738.9
   998.7  2747.9  1059.2 2777.44  1109.6 2807.49  1119.7 2812.53  1139.9 2820.71
  1180.3  2834.3  1250.9 2851.53  1321.5 2874.52    1382  2892.7  1432.5 2906.25
#Mann= 3 , 0 , 0
       0      .1       0   644.3    .045       0   669.7      .1       0
Bank Sta=644.3,669.7
XS Rating Curve= 0 ,0
Exp/Cntr=0.3,0.1

Type RM Length L Ch R = 1 ,112734.4,897.6,889.9,894.4
XS GIS Cut Line= 3
     2128718.576      390060.788     2127802.098      389496.454
     2127206.162      389663.497
#Sta/Elev= 30
       0  2848.9    90.5 2831.34   110.6 2825.63     171 2796.93   211.2  2779.9
   321.9 2744.33   402.4 2715.32   422.5 2706.17   462.7 2683.94   502.9 2667.45
   533.1 2660.71   563.3 2656.42     684 2648.52   731.3 2643.05   744.4 2642.56
   757.3 2644.28   895.2 2661.92   955.6 2665.21   995.8 2663.16  1096.3 2679.93
  1126.2 2689.64    1236 2716.55  1285.9 2738.72  1335.8 2765.14  1365.8 2775.84
  1465.6 2800.13  1535.5 2822.26  1565.4 2827.72  1615.3 2832.08  1695.2  2856.6
#Mann= 3 , 0 , 0
       0      .1       0   731.3    .045       0   757.3      .1       0
Bank Sta=731.3,757.3
XS Rating Curve= 0 ,0
Exp/Cntr=0.3,0.1

Type RM Length L Ch R = 1 ,111844.5,146.7,150,153.4
XS GIS Cut Line= 4
     2129006.257      389602.973     2128589.046      388935.038
     2128363.012      388871.881     2127459.305      389002.426
#Sta/Elev= 30
       0 2879.54    40.4 2872.45   131.2 2842.29   151.4 2833.16   191.8 2808.66
   252.4 2780.72     313 2759.62   434.2 2721.77   585.6 2686.28   706.8 2644.39
   757.2  2630.2   836.4 2617.61   930.1 2609.13     944  2608.3   956.3 2610.47
  1022.2 2633.51  1062.4 2641.34  1112.5 2647.46  1162.7 2648.24  1202.8 2651.72
    1253 2658.36  1293.1 2667.03  1373.4 2697.91  1423.6  2719.5    1554 2771.59
  1694.5 2812.95  1724.6 2818.43  1764.7 2819.41    1835 2828.18  1935.3  2846.1
#Mann= 3 , 0 , 0
       0      .1       0   930.1    .045       0   956.3      .1       0
Bank Sta=930.1,956.3
XS Rating Curve= 0 ,0
Exp/Cntr=0.3,0.1

Type RM Length L Ch R = 1 ,111694.5,235.8,253.1,270.4
XS GIS Cut Line= 4
     2129040.942      389483.062     2128680.218      388835.938
     2128331.386       388689.27     2127491.017      388895.398
#Sta/Elev= 30
       0 2846.22      40 2833.55   110.1 2804.81   190.2 2780.06   270.3 2743.13
   340.4 2721.53   410.5 2705.42   470.6 2684.63   510.6  2667.7   610.7 2635.89
   740.9 2620.41   957.7 2603.53     960 2603.46     984 2604.58  1019.7  2606.6
  1039.6 2610.06  1079.4 2624.57  1119.3 2631.52  1270.2 2679.48  1390.9 2700.36
  1451.3 2714.47  1551.9 2725.53  1632.4 2740.38  1753.2  2772.9  1803.5 2793.54
  1833.6 2795.91  1863.8 2805.34  1873.9 2806.28  1924.2 2796.81  1984.6 2803.11
#Mann= 3 , 0 , 0
       0      .1       0   957.7    .045       0     984      .1       0
Bank Sta=957.7,984
XS Rating Curve= 0 ,0
Exp/Cntr=0.3,0.1

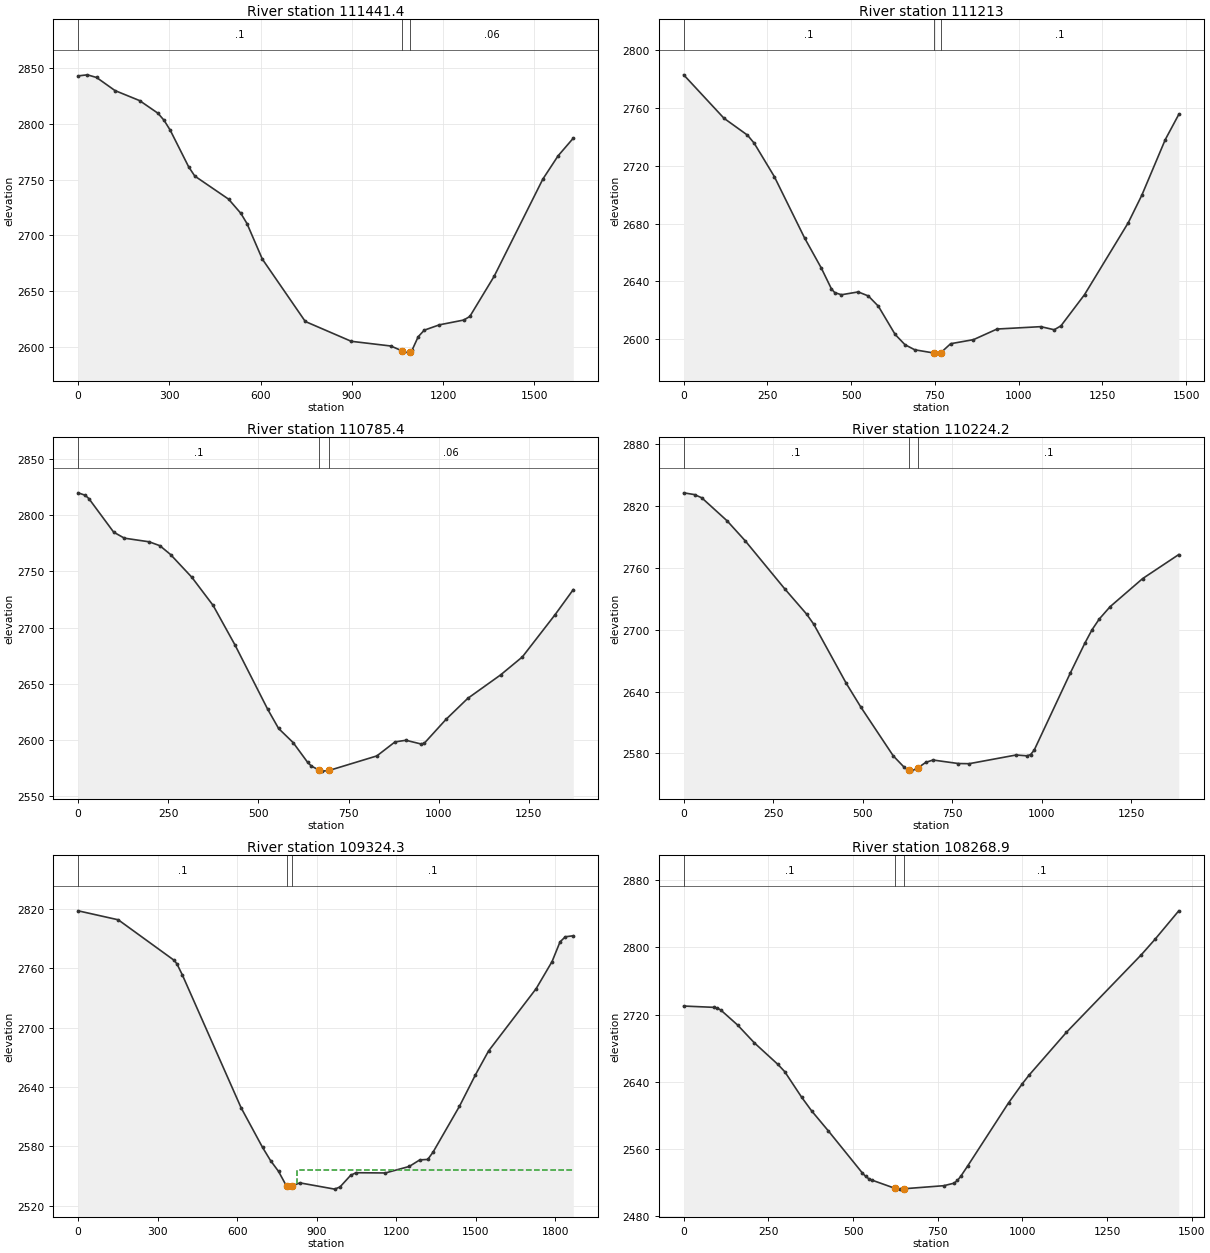
Type RM Length L Ch R = 1 ,111441.4,205.7,228.4,251.1
XS GIS Cut Line= 3
     2129155.028      389518.564     2128731.784       388749.31
     2128361.059      388097.452
#Sta/Elev= 30
       0 2843.27    30.3 2844.22    60.6 2841.82   121.1 2830.08   201.8  2821.1
   262.4 2809.72   282.6 2803.31   302.8 2794.42   363.3  2761.6   383.5 2753.28
   494.5 2732.58   534.9 2719.82   555.1 2710.63   605.5 2678.75   746.8 2622.69
     898 2604.89    1028 2600.67  1065.7 2596.23    1088 2594.27  1092.1 2595.39
    1098 2596.99    1118 2608.96    1138 2614.88    1188  2619.7    1268    2624
    1288 2627.27  1367.9 2663.33  1527.9 2750.56  1577.9 2771.42  1627.9 2787.29
#Mann= 3 , 0 , 0
       0      .1       0  1065.7    .045       0  1092.1     .06       0
Bank Sta=1065.7,1092.1
XS Rating Curve= 0 ,0
Exp/Cntr=0.3,0.1

Type RM Length L Ch R = 1 ,111213  ,460.1,427.6,395.1
XS GIS Cut Line= 4
     2129089.501      389278.916      2128813.52      388711.201
     2128891.075      388490.703     2128500.847      388018.363
#Sta/Elev= 30
       0 2783.12   120.2 2753.01   190.4 2741.29   210.4 2735.71   270.5 2712.56
   360.7 2670.05   410.8 2649.09   440.9 2634.71   450.9 2632.06   470.9  2630.6
     521 2632.56   551.1 2629.76   581.1 2622.64   631.2 2603.06   660.5 2595.95
   689.7 2592.42   748.1 2590.14   757.8 2590.11   767.6 2590.44   796.8 2596.64
     865 2599.46   935.3 2606.82  1065.9 2608.47    1106 2606.32  1126.1 2609.05
  1196.4 2630.66    1327 2680.58  1367.2 2699.52  1437.5 2738.24  1477.7 2755.66
#Mann= 3 , 0 , 0
       0      .1       0   748.1    .045       0   767.6      .1       0
Bank Sta=748.1,767.6
XS Rating Curve= 0 ,0
Exp/Cntr=0.3,0.1

Type RM Length L Ch R = 1 ,110785.4,552.7,561.1,569.6
XS GIS Cut Line= 3
     2129513.395      388857.438      2129343.48      388523.786
     2128586.583      387871.928
#Sta/Elev= 30
       0 2820.06    19.7 2817.86    29.6 2814.96    98.5 2785.03   128.1 2779.69
   197.1 2776.43   226.6 2772.98   256.2 2765.13   315.3 2744.86   374.4 2719.75
     435 2684.58   525.8 2627.26     556 2610.18   596.4  2597.6   636.8 2579.92
   646.9 2576.72   669.4 2572.92   677.1 2572.21     696  2572.8   828.5 2585.75
   878.9 2598.24   909.2 2599.69   949.6  2596.5   959.6 2596.86  1020.2 2618.26
  1080.7 2637.02  1171.5 2657.84  1232.1 2673.91  1322.9 2711.54  1373.3 2733.86
#Mann= 3 , 0 , 0
       0      .1       0   669.4    .045       0     696     .06       0
Bank Sta=669.4,696
XS Rating Curve= 0 ,0
Exp/Cntr=0.3,0.1

Type RM Length L Ch R = 1 ,110224.2,885.4,900,914.6
XS GIS Cut Line= 2
     2129856.316      388529.965      2129147.47      387342.957
#Sta/Elev= 30
       0 2832.35    30.3 2830.63    50.5 2827.53   121.1 2805.29   171.6 2785.98
   282.6 2739.22   343.1    2715   363.3  2705.1   454.1 2647.84   494.5 2625.02
   585.3 2577.66   615.6 2566.72   627.9 2563.53   635.8 2562.91   654.7 2566.22
   676.1 2571.39   696.3 2573.66     767 2570.27   797.2 2570.11   928.4 2578.53
   958.7 2577.74   968.8 2578.95   978.9 2583.27  1079.8 2657.95  1120.2 2686.72
  1140.4  2699.8  1160.5 2710.14  1190.8  2722.1  1281.6  2749.3  1382.6  2772.6
#Mann= 3 , 0 , 0
       0      .1       0   627.9    .045       0   654.7      .1       0
Bank Sta=627.9,654.7
XS Rating Curve= 0 ,0
Exp/Cntr=0.3,0.1

Type RM Length L Ch R = 1 ,109324.3,1060.8,1055.3,1049.9
XS GIS Cut Line= 3
     2130326.617      388498.593     2130349.885      387339.094
     2129693.295      387071.303
#Sta/Elev= 30
       0 2818.12   151.3 2809.05     363 2767.95   373.1 2764.34   393.3  2753.3
   615.2 2618.94   695.8 2579.06   726.1 2565.68   756.4  2554.7   786.6 2539.76
   796.7 2538.85   806.8 2540.01     837 2543.11   968.1 2536.78   988.3 2538.97
  1028.6 2550.76  1048.8 2553.37  1159.7 2553.12  1249.6 2559.69  1289.6 2566.35
  1319.5 2566.79  1339.5 2574.14  1439.4 2620.61  1499.3 2652.18  1549.2 2676.48
    1729 2739.54  1788.9 2766.88  1818.9 2786.73  1838.9 2791.89  1868.8  2792.9
#Mann= 3 , 0 , 0
       0      .1       0   786.6    .045       0   806.8      .1       0
#XS Ineff= 2 , 0
                          827.34         2555.66
Permanent Ineff=
       F       F
Bank Sta=786.6,806.8
XS Rating Curve= 0 ,0
Exp/Cntr=0.3,0.1

Type RM Length L Ch R = 1 ,108268.9,704.4,713.4,722.5
XS GIS Cut Line= 3
     2131156.498      387988.554     2131337.085      387482.911
     2131163.121      386574.391
#Sta/Elev= 30
       0 2730.18    89.5 2728.62    99.4 2727.69   109.4 2725.49   159.1 2707.64
   208.8 2686.32   278.4 2660.67   298.3 2652.15     348 2621.88   377.8 2605.45
   427.6 2581.42     527 2531.85   536.9 2527.66     547 2524.61     557  2522.9
   624.5  2513.2   637.5 2512.33     652 2512.82   768.2 2516.42   798.3  2519.4
   808.4 2522.62   818.4 2527.73   838.6 2539.87   959.2 2614.89   999.4  2637.4
  1019.6 2647.82  1130.2 2698.91  1351.4 2791.22  1391.6 2809.48    1462 2843.47
#Mann= 3 , 0 , 0
       0      .1       0   624.5    .045       0     652      .1       0
Bank Sta=624.5,652
XS Rating Curve= 0 ,0
Exp/Cntr=0.3,0.1

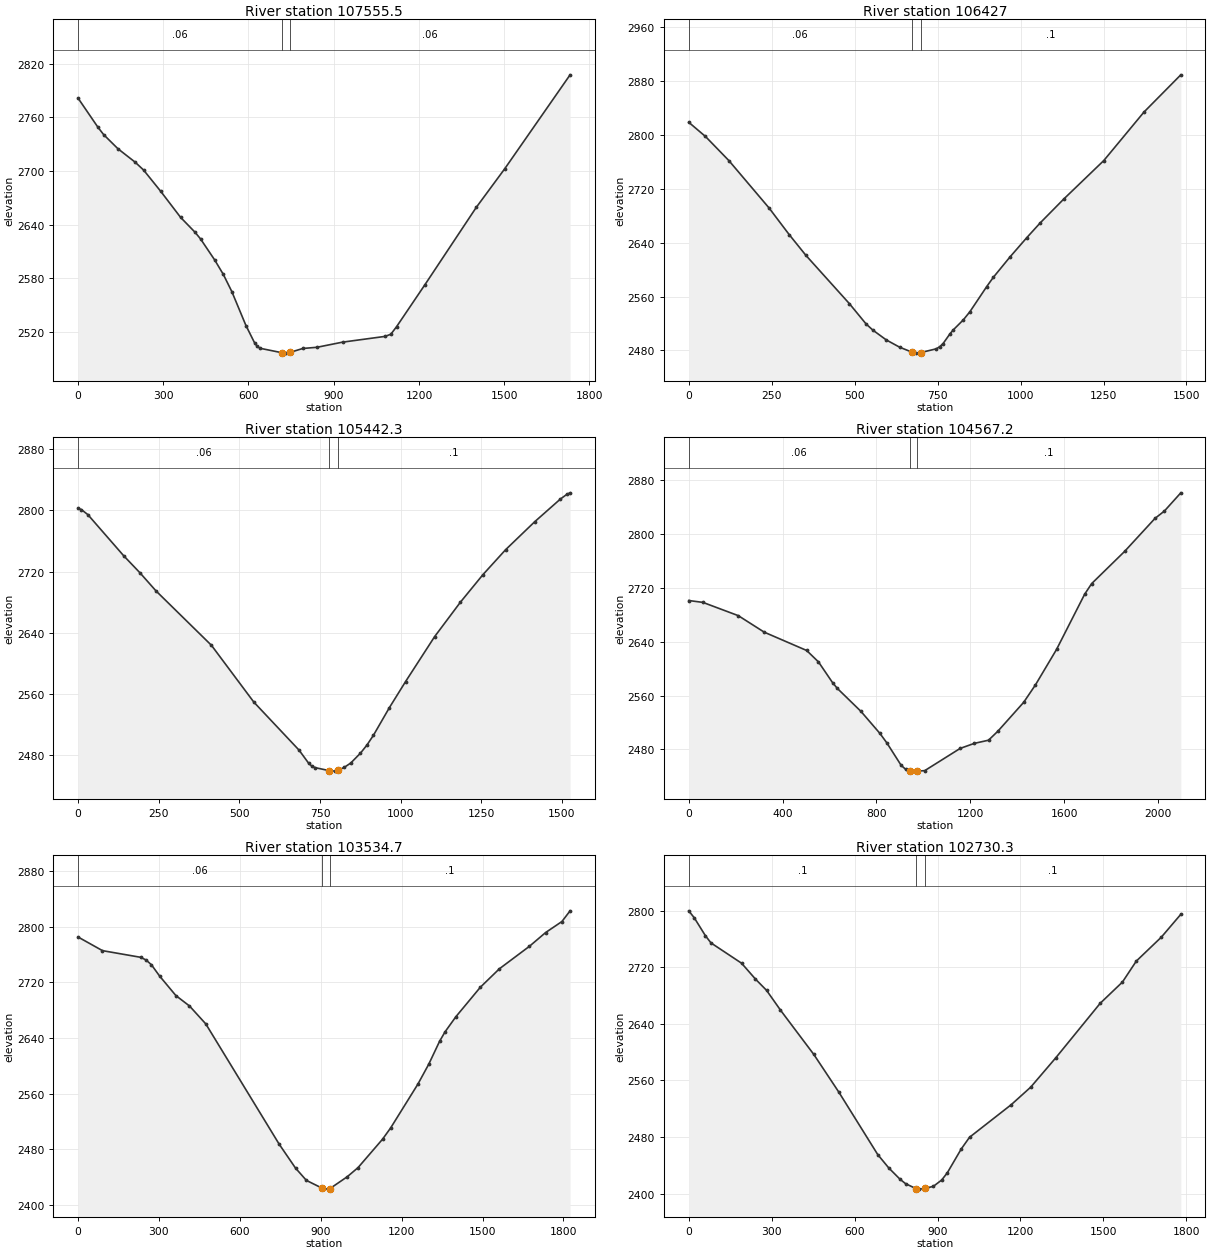
Type RM Length L Ch R = 1 ,107555.5,1122.7,1128.5,1134.2
XS GIS Cut Line= 4
     2132130.094      388066.559     2131963.268      387593.885
     2132049.771      387040.887     2132510.087      386552.766
#Sta/Elev= 30
       0 2781.42    70.2 2748.77    90.2 2740.57   140.4  2724.8   200.5  2709.9
   230.6 2701.02   290.7 2677.31   360.9 2648.06     411 2631.66   431.1 2623.99
   481.2  2600.3   511.2 2584.34   541.2 2565.11   591.2 2526.94   621.2 2507.84
   631.2 2503.62   641.2 2501.58   718.4 2496.59   731.1 2496.19   746.2 2497.02
   791.1 2501.39   841.1 2502.73     931 2508.47    1081 2514.92    1101 2517.35
  1121.1 2525.73  1221.2 2572.82  1401.4 2659.07  1501.6 2702.28  1731.9 2807.44
#Mann= 3 , 0 , 0
       0     .06       0   718.4    .045       0   746.2     .06       0
Bank Sta=718.4,746.2
XS Rating Curve= 0 ,0
Exp/Cntr=0.3,0.1

Type RM Length L Ch R = 1 ,106427  ,993,984.8,976.4
XS GIS Cut Line= 2
     2132809.757      388292.083     2133350.397      386911.133
#Sta/Elev= 30
       0 2819.05    50.4 2797.96   121.1 2762.04   242.1 2691.66   302.6 2652.21
   353.1 2621.29   484.2 2549.48   534.7 2519.21   554.9 2510.18   595.2 2495.64
   635.6 2484.78   672.2 2477.55     686 2475.97   700.3  2476.9   746.6 2482.45
   756.6 2485.66   766.7 2490.27   786.9 2504.39     797  2510.4   827.3 2525.27
   847.4 2537.52   897.9 2574.76     918 2588.64   968.5 2619.07  1018.9 2647.63
  1059.3 2669.53  1129.9 2704.81    1251 2762.21    1372 2834.24    1483 2889.56
#Mann= 3 , 0 , 0
       0     .06       0   672.2    .045       0   700.3      .1       0
Bank Sta=672.2,700.3
XS Rating Curve= 0 ,0
Exp/Cntr=0.3,0.1

Type RM Length L Ch R = 1 ,105442.3,873.6,875,876.5
XS GIS Cut Line= 3
     2133853.965      388687.523     2133964.623      388092.392
     2134011.523       387173.73
#Sta/Elev= 30
       0 2802.86    10.1 2801.22    30.3 2794.62   141.2 2740.92   191.7 2718.58
   242.1  2694.6   413.6 2623.61   544.8 2549.42   685.3 2486.44   715.3 2469.14
   725.3 2465.39   735.3  2463.6     777 2459.85   795.3 2459.07   805.5 2460.12
   825.3    2464   845.3 2469.66   875.3  2482.5   895.3 2493.05   915.3  2505.7
   965.3 2542.25  1015.3 2576.23  1105.2 2634.92  1185.2 2680.02  1255.2 2716.12
  1325.2 2748.61  1415.2 2785.13  1495.2 2814.96  1515.2  2821.1  1525.2 2823.06
#Mann= 3 , 0 , 0
       0     .06       0     777    .045       0   805.5      .1       0
Bank Sta=777,805.5
XS Rating Curve= 0 ,0
Exp/Cntr=0.3,0.1

Type RM Length L Ch R = 1 ,104567.2,1004.7,1032.6,1060.4
XS GIS Cut Line= 4
     2134218.511      388449.641      2134811.67      388017.129
     2134870.369      387476.488     2135682.874       387368.36
#Sta/Elev= 30
       0 2700.93    60.3 2698.17   211.2 2678.49   321.8 2653.99   502.8 2626.79
   553.1 2609.84   613.4 2578.96   633.5 2570.53   734.1 2536.47   814.7 2503.89
   844.9 2489.54   905.3 2456.52   925.4 2450.27   942.4  2448.1   955.7 2447.83
   971.2 2447.83    1006 2448.54  1157.1 2481.54  1217.5 2489.02  1277.9 2493.71
  1317.9 2507.09  1427.9 2549.95  1477.8 2575.67  1567.8  2628.3  1687.8 2710.34
  1717.7 2726.08  1857.7 2773.66  1987.6 2822.79  2027.6 2833.67  2097.6  2860.7
#Mann= 3 , 0 , 0
       0     .06       0   942.4    .045       0   971.2      .1       0
Bank Sta=942.4,971.2
XS Rating Curve= 0 ,0
Exp/Cntr=0.3,0.1

Type RM Length L Ch R = 1 ,103534.7,802,804.4,806.7
XS GIS Cut Line= 2
     2134246.315      388987.192     2135905.309      388227.206
#Sta/Elev= 30
       0 2785.08    90.7 2765.45   231.9 2755.91     252 2752.13   272.2 2745.18
   302.4 2729.02   362.9 2700.91   413.4 2685.95   473.8 2660.22     746 2487.37
   806.5 2453.09   846.9 2435.38   905.2 2424.19   927.5 2422.82   934.3 2423.63
   998.1 2440.52  1038.4  2453.7  1129.2 2494.51  1159.4 2510.78  1260.2 2573.57
  1300.5 2602.19  1340.9 2635.25    1361 2648.76  1401.4 2670.59  1492.1 2712.92
  1562.7 2739.42  1673.6 2771.58    1734 2791.44  1794.5 2807.29  1824.8 2822.66
#Mann= 3 , 0 , 0
       0     .06       0   905.2    .045       0   934.3      .1       0
Bank Sta=905.2,934.3
XS Rating Curve= 0 ,0
Exp/Cntr=0.3,0.1

Type RM Length L Ch R = 1 ,102730.3,810.1,813,815.9
XS GIS Cut Line= 2
     2134607.772      389611.245     2136288.391      389024.264
#Sta/Elev= 30
       0 2799.66    20.1 2789.75    60.3 2764.48    80.5 2754.29   191.1 2725.62
   241.4 2703.16   281.6 2687.21   331.9 2659.27   452.6 2596.56   543.1 2543.28
   683.9 2454.98   724.1 2435.96   764.4 2420.19   784.5 2413.91   823.7 2406.65
   834.8  2406.2   853.1 2407.11   885.1 2410.17   915.2 2419.12   935.4 2429.24
   985.6 2462.81  1015.8  2479.5  1166.7 2525.59  1237.1 2550.35  1327.6 2591.73
  1488.5  2668.9    1569 2698.95  1619.3 2728.64  1709.8 2762.45  1780.2 2794.71
#Mann= 3 , 0 , 0
       0      .1       0   823.7    .045       0   853.1      .1       0
Bank Sta=823.7,853.1
XS Rating Curve= 0 ,0
Exp/Cntr=0.3,0.1

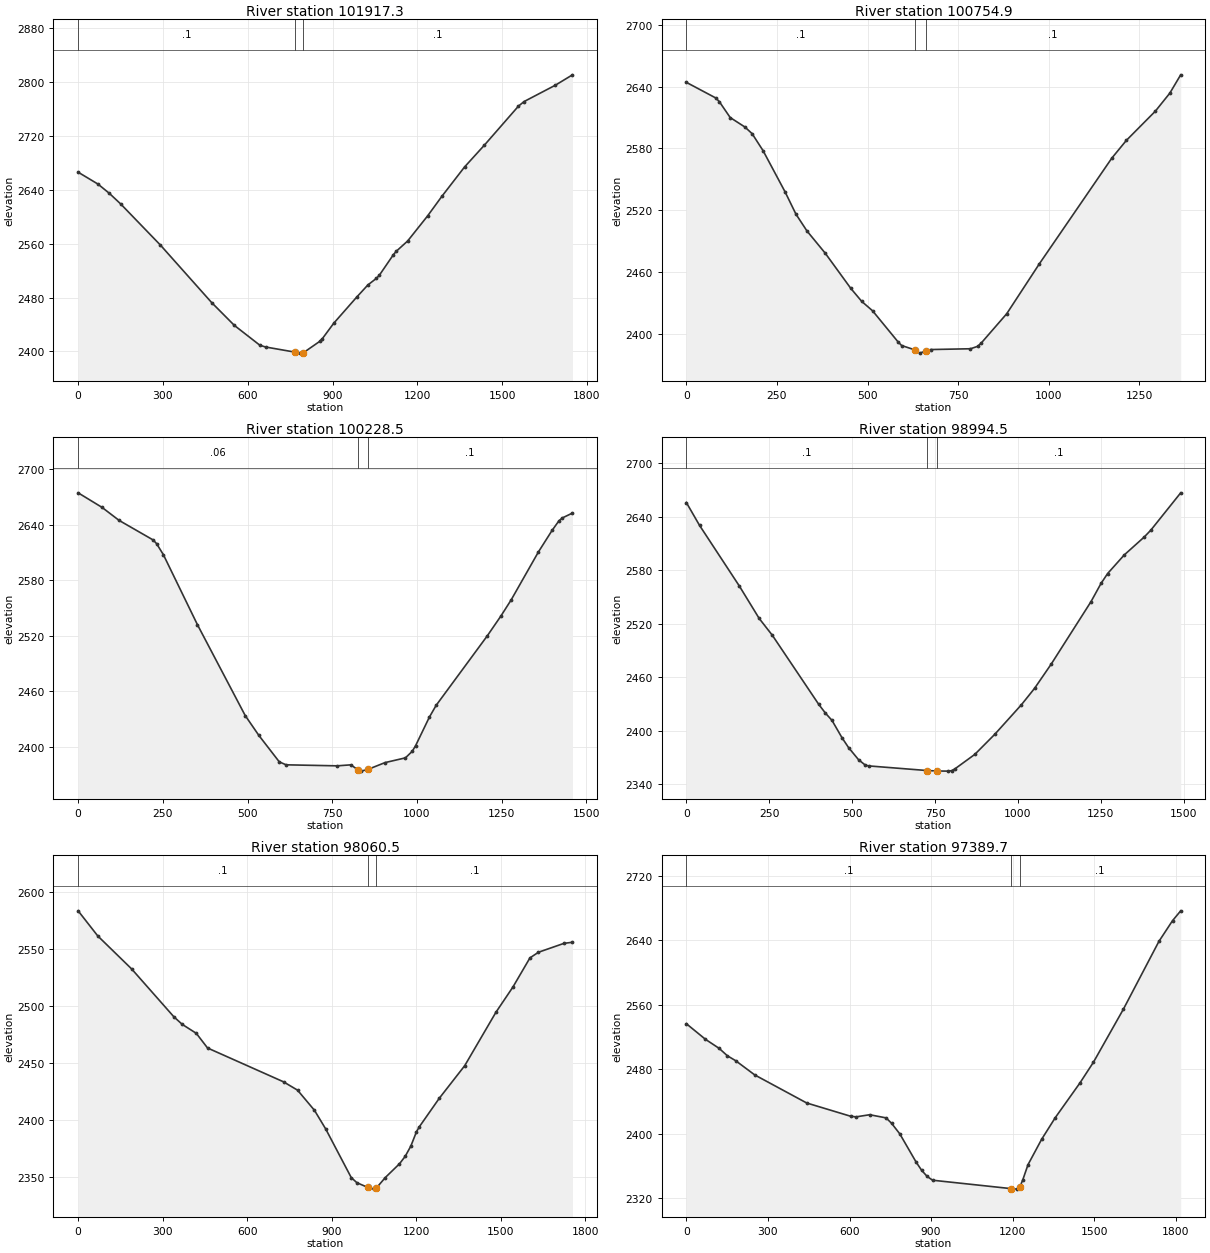
Type RM Length L Ch R = 1 ,101917.3,1160.8,1162.4,1163.9
XS GIS Cut Line= 3
       2134861.1       389981.97     2135333.775       390179.69
      2136538.63      389901.646
#Sta/Elev= 30
       0 2666.31    70.3  2648.6   110.5 2634.83   150.7 2619.02   291.3 2557.85
   472.2 2472.54   552.6 2438.58     643 2409.02   663.2 2406.42   767.5 2398.76
   783.8 2397.31   797.2 2397.99   854.2 2414.64   864.2 2418.94   904.4 2441.81
   984.8 2480.25  1025.1 2498.68  1055.2 2508.47  1065.3 2512.91  1115.5 2543.76
  1125.6 2548.78  1165.8 2564.04  1236.2 2601.23  1286.4 2630.18  1366.9 2673.98
  1437.2 2706.49  1557.9 2764.59    1578  2771.4  1688.6  2795.7  1748.9 2811.06
#Mann= 3 , 0 , 0
       0      .1       0   767.5    .045       0   797.2      .1       0
Bank Sta=767.5,797.2
XS Rating Curve= 0 ,0
Exp/Cntr=0.3,0.1

Type RM Length L Ch R = 1 ,100754.9,542.3,526.4,510.5
XS GIS Cut Line= 3
     2134728.257       391118.86     2135197.842      391236.256
     2136065.956      391091.055
#Sta/Elev= 30
       0 2644.04    80.7 2628.98    90.8 2625.43     121  2609.9   161.4 2600.77
   181.5 2594.28   211.8 2577.73   272.3 2537.92   302.5 2516.18   332.8 2499.93
   383.2 2478.38   453.8 2444.23     484  2431.6     514 2422.45   584.1 2392.39
   594.1  2388.8   630.4 2384.61   644.1 2381.43   660.5 2383.48   674.1  2384.9
   784.1 2385.67   804.1 2388.03   814.1 2391.34   884.1 2419.64   974.1 2468.03
  1174.2 2570.59  1214.2 2587.72  1294.2 2616.06  1334.2 2633.57  1364.2 2651.33
#Mann= 3 , 0 , 0
       0      .1       0   630.4    .045       0   660.5      .1       0
Bank Sta=630.4,660.5
XS Rating Curve= 0 ,0
Exp/Cntr=0.3,0.1

Type RM Length L Ch R = 1 ,100228.5,1238.3,1234,1224.2
XS GIS Cut Line= 2
     2135105.161      392110.548      2136192.62      391137.396
#Sta/Elev= 30
       0 2674.35    70.4 2658.68   120.8 2644.62   221.4 2623.48   231.5 2619.54
   251.6 2607.62   352.2 2532.01   493.2 2433.96   533.4 2412.58   593.8 2383.98
   613.9 2380.79   764.9 2379.69   805.1 2380.76   825.4 2375.52   835.3 2373.98
   855.7 2375.87   905.8 2383.17   966.2 2388.31   986.3 2395.39   996.4  2401.6
  1036.6 2432.09  1056.7 2444.91  1207.7 2519.94    1248 2541.39  1278.2 2558.74
  1358.7 2610.53  1398.9  2633.7  1419.1 2644.02  1429.1 2647.22  1459.3 2652.52
#Mann= 3 , 0 , 0
       0     .06       0   825.4    .045       0   855.7      .1       0
Bank Sta=825.4,855.7
XS Rating Curve= 0 ,0
Exp/Cntr=0.3,0.1

Type RM Length L Ch R = 1 ,98994.5 ,959.8,934,913.8
XS GIS Cut Line= 3
     2136717.814      392830.372     2136600.418      392407.128
     2137048.377      391455.601
#Sta/Elev= 30
       0 2655.85    39.9 2630.14   159.7  2562.3   219.6 2525.92   259.5 2506.92
   399.3 2429.55   419.3 2419.82   439.2 2411.63   469.3 2392.25   489.3 2381.08
   519.4 2367.52   539.4 2361.56   549.4  2360.6   726.5 2355.37   757.2 2354.88
   789.8 2354.73   799.8 2355.21   809.8 2357.22   869.9 2373.48     930 2395.93
  1010.2 2428.99  1050.2 2447.54  1100.3 2474.67  1220.5 2544.78  1250.5 2565.06
  1270.6 2576.26  1320.6 2597.05  1380.7 2617.09  1400.8 2624.86  1490.9  2666.7
#Mann= 3 , 0 , 0
       0      .1       0   726.5    .045       0   757.2      .1       0
Bank Sta=726.5,757.2
XS Rating Curve= 0 ,0
Exp/Cntr=0.3,0.1

Type RM Length L Ch R = 1 ,98060.5 ,632.2,670.8,709.4
XS GIS Cut Line= 3
     2137215.203      393049.718     2137663.162      392305.179
     2137382.029      391464.869
#Sta/Elev= 30
       0 2583.43    69.9 2561.34   189.8  2532.5   339.6 2490.54   369.5 2483.83
   419.5 2475.96   459.4 2463.11   729.1 2433.42     779 2426.09     839 2408.43
     879 2392.03   969.6 2349.41   989.7  2344.9  1027.6 2340.86  1050.2 2339.28
  1058.6  2340.2  1090.4 2349.42  1140.8  2361.5  1160.9 2367.97  1181.1 2377.02
  1201.2 2389.62  1211.3 2393.98  1281.8 2418.88  1372.4 2447.57  1483.1 2494.39
  1543.6  2516.6    1604 2542.15  1634.2 2547.09  1724.8 2554.89    1755 2555.86
#Mann= 3 , 0 , 0
       0      .1       0  1027.6    .045       0  1058.6      .1       0
Bank Sta=1027.6,1058.6
XS Rating Curve= 0 ,0
Exp/Cntr=0.3,0.1

Type RM Length L Ch R = 1 ,97389.7 ,401.6,414.2,426.7
XS GIS Cut Line= 3
     2137304.795      393031.182      2137870.15      392323.715
     2138698.102      391940.633
#Sta/Elev= 30
       0 2536.64    70.4 2517.22   120.8 2505.96   150.9 2496.78   181.1 2490.74
   251.6 2472.99   442.7 2438.14   603.7 2421.72   623.9  2420.9   674.2 2423.56
   734.6 2419.64   754.7 2412.91   784.9  2399.8   845.2 2364.58   865.4 2354.46
   885.5 2346.92   905.6  2342.2  1194.7 2331.75  1216.4 2331.14    1226 2333.89
  1236.4 2341.89  1256.5 2361.58  1306.6 2393.09  1356.7 2419.96    1447 2462.85
  1497.1 2488.83  1607.4 2554.84  1737.7 2638.84  1787.8 2664.61  1817.9 2676.86
#Mann= 3 , 0 , 0
       0      .1       0  1194.7    .045       0    1226      .1       0
Bank Sta=1194.7,1226
XS Rating Curve= 0 ,0
Exp/Cntr=0.3,0.1

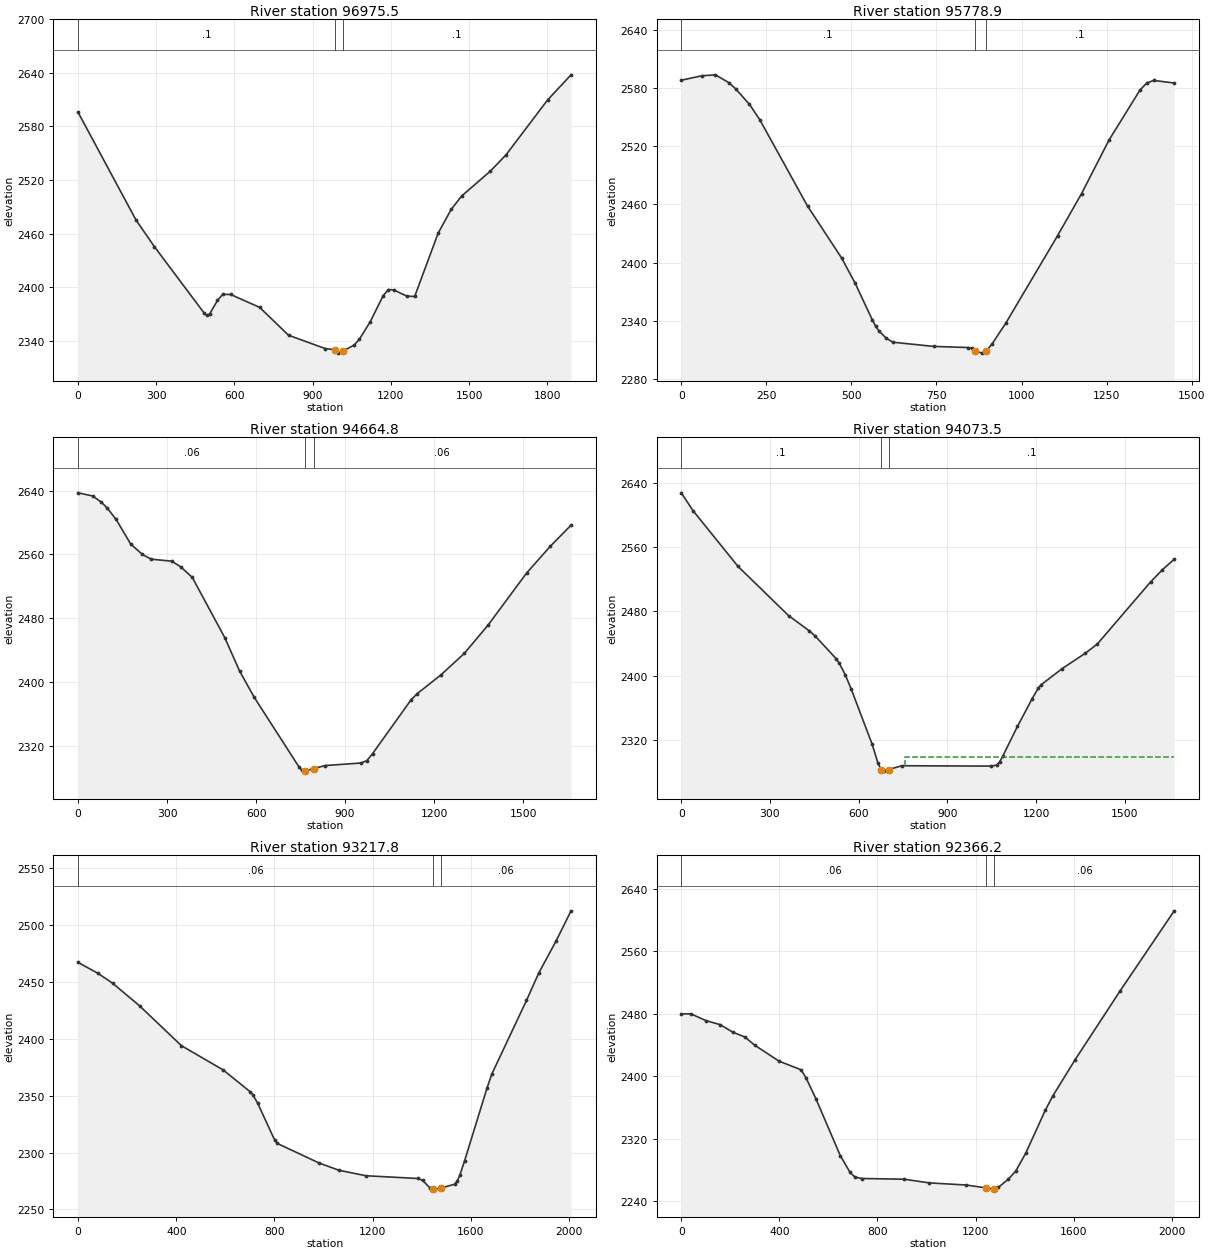
Type RM Length L Ch R = 1 ,96975.5 ,1234.1,1196.6,1159
XS GIS Cut Line= 4
     2137666.251      393324.672     2137962.831       392595.58
     2138466.399      392617.206     2138725.906      392076.565
#Sta/Elev= 30
       0 2595.78     222 2475.33   292.6 2445.44   484.4 2370.68   494.5 2368.32
   504.6 2369.99   534.8 2385.16     555 2392.01   585.3 2391.82   696.3  2377.4
   807.3 2346.18   948.4 2331.24   984.8 2329.95   998.8 2326.17  1016.2 2328.45
  1059.3 2335.26  1079.4 2341.94  1119.8 2360.86  1170.2 2390.46  1190.3 2397.29
  1210.5    2397  1260.9 2389.98  1291.1 2389.62  1381.1 2460.45  1431.1 2487.08
    1471 2501.98    1581 2529.82    1641 2547.97  1800.9  2609.6  1890.8 2637.73
#Mann= 3 , 0 , 0
       0      .1       0   984.8    .045       0  1016.2      .1       0
Bank Sta=984.8,1016.2
XS Rating Curve= 0 ,0
Exp/Cntr=0.3,0.1

Type RM Length L Ch R = 1 ,95778.9 ,1081.1,1114.2,1147.2
XS GIS Cut Line= 3
     2138623.957      393658.324     2138957.609       393086.79
     2139108.989      392314.447
#Sta/Elev= 30
       0 2587.95    60.2 2592.53   100.3 2593.51   140.4 2585.31   160.4 2578.85
   200.5 2563.08   230.6 2547.34     371 2458.32   471.3 2404.72   511.4 2378.48
   561.5 2340.97   571.6 2334.36   581.6  2329.4   601.6 2322.32   621.7 2317.98
   742.5  2313.6   843.4  2312.5   853.5 2311.65   863.2 2309.26   883.8 2306.71
   895.1 2308.46     914 2316.47   954.4 2337.96  1105.8 2427.66  1176.4 2471.11
  1257.1 2526.28  1347.9  2577.7  1368.1 2585.09  1388.3 2587.72  1448.8 2585.08
#Mann= 3 , 0 , 0
       0      .1       0   863.2    .045       0   895.1      .1       0
Bank Sta=863.2,895.1
XS Rating Curve= 0 ,0
Exp/Cntr=0.3,0.1

Type RM Length L Ch R = 1 ,94664.8 ,605.8,591.3,576.8
XS GIS Cut Line= 4
     2138706.855      394136.662     2138809.834      393765.938
     2139555.403      393708.269     2139897.294      393304.591
#Sta/Elev= 30
       0 2637.09    49.3 2633.13    78.9  2625.3    98.7 2617.78   128.2 2603.83
   177.6 2572.83     217 2559.88   246.6 2553.99   315.7 2551.48   345.3 2544.59
   384.8 2531.26   494.4 2455.86   544.3 2414.02   594.1 2380.85   743.7 2294.37
   753.7 2289.85   763.6 2288.59   793.6 2291.84   833.4 2295.59   953.1 2298.76
     973 2301.57     993 2310.65  1122.6 2377.99  1142.5  2385.4  1222.4 2408.91
  1302.2 2436.12  1382.1 2471.52  1511.8 2536.64  1591.7 2570.15  1661.6 2596.58
#Mann= 3 , 0 , 0
       0     .06       0   763.6    .045       0   793.6     .06       0
Bank Sta=763.6,793.6
XS Rating Curve= 0 ,0
Exp/Cntr=0.3,0.1

Type RM Length L Ch R = 1 ,94073.5 ,891.1,855.7,820.4
XS GIS Cut Line= 3
     2138829.594      394702.478     2139493.294      394193.044
     2139894.366      393465.775
#Sta/Elev= 30
       0 2627.53    40.3  2605.1   191.5  2536.2   362.9  2474.8   433.5 2455.71
   453.6  2449.1   524.2 2421.09   534.3 2415.58   554.4 2401.48   574.6 2383.56
   645.1 2315.33   665.3 2291.38   675.4 2283.26   685.5 2281.34  701.09  2283.3
     746 2288.06  1046.8 2287.59  1066.8 2288.87  1076.8 2292.98  1086.8  2299.6
  1136.9 2336.88  1186.9 2371.58  1206.9 2384.28  1216.9 2388.76    1287 2408.53
    1367 2428.12    1407 2439.44  1587.2 2516.68  1627.2 2531.91  1667.2 2544.95
#Mann= 3 , 0 , 0
       0      .1       0   675.4    .045       0  701.09      .1       0
#XS Ineff= 2 , 0
                          758.33         2298.75
Permanent Ineff=
       F       F
Bank Sta=675.4,701.09
XS Rating Curve= 0 ,0
Exp/Cntr=0.3,0.1

Type RM Length L Ch R = 1 ,93217.8 ,838.7,851.5,864.2
XS GIS Cut Line= 3
      2140012.63       395528.94     2140185.837       394268.46
     2139933.016      393577.715
#Sta/Elev= 30
       0 2467.32    80.2 2457.88   140.3 2449.12   250.5 2429.17   420.8 2394.15
   591.1 2372.76   701.3 2353.53   711.3 2351.13   731.3  2343.6   801.5 2310.74
   811.5 2308.12   981.8 2290.89  1061.9 2284.57  1172.1  2279.7  1383.2 2277.28
  1403.3 2275.62  1433.5 2268.94  1446.8 2268.09  1453.7 2267.92  1479.5 2268.95
  1534.3 2272.27  1544.4 2274.98  1554.5 2279.97  1574.6 2292.96  1665.3 2356.61
  1685.4 2369.24  1826.5 2433.94  1876.9 2458.21  1947.4 2486.38  2007.9 2512.74
#Mann= 3 , 0 , 0
       0     .06       0  1446.8    .045       0  1479.5     .06       0
Bank Sta=1446.8,1479.5
XS Rating Curve= 0 ,0
Exp/Cntr=0.3,0.1

Type RM Length L Ch R = 1 ,92366.2 ,715.9,718,720.2
XS GIS Cut Line= 3
     2141174.235      394989.329     2140837.696      394309.928
      2140935.19       393062.01
#Sta/Elev= 30
       0 2479.91    39.9 2479.84    99.8  2471.4   159.6 2466.02   209.5 2456.56
   259.4 2450.29   299.3 2439.81     399  2419.3   488.8 2408.24   508.8 2397.98
   548.7  2371.4   648.4 2298.31   688.4 2276.78   708.3 2270.77   738.2 2269.02
   909.6 2268.14  1010.6 2263.42    1162 2260.68  1243.8 2256.92    1273 2255.42
  1276.8 2255.59  1293.2 2257.74  1333.6 2268.18  1363.9 2278.68  1404.2 2301.27
    1485 2357.02  1515.3 2375.06  1606.1 2421.34  1787.8 2508.71  2009.9 2611.92
#Mann= 3 , 0 , 0
       0     .06       0  1243.8    .045       0  1276.8     .06       0
Bank Sta=1243.8,1276.8
XS Rating Curve= 0 ,0
Exp/Cntr=0.3,0.1