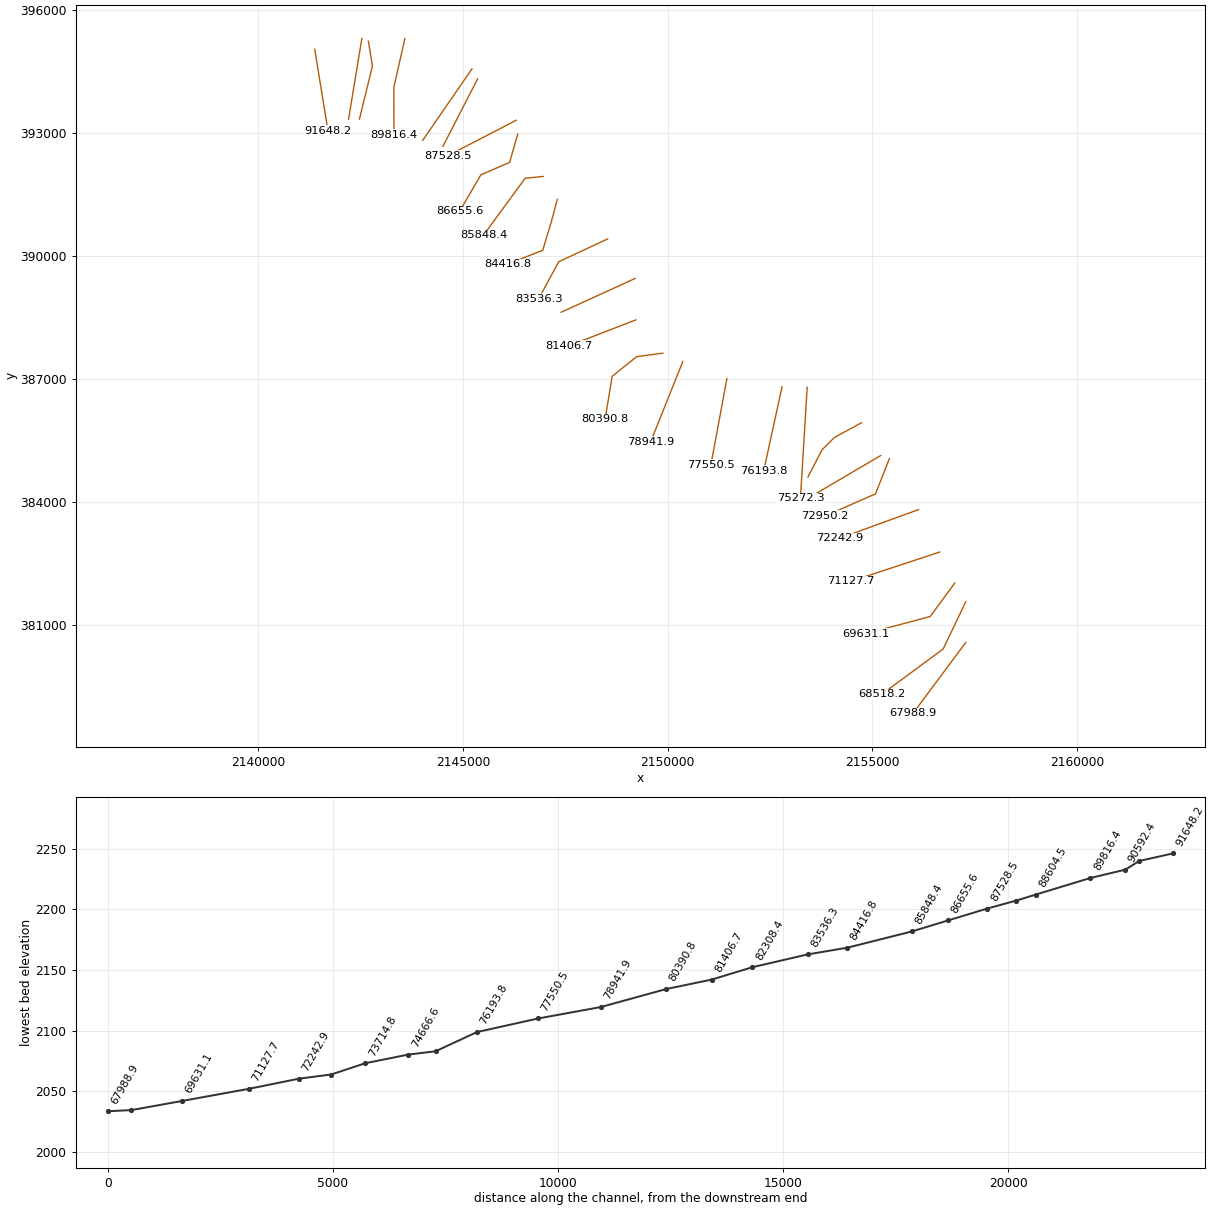
HEC-RAS study SpringCk.prj: SpringCk

--- SpringCk.g01 (geometry) --- (continued)

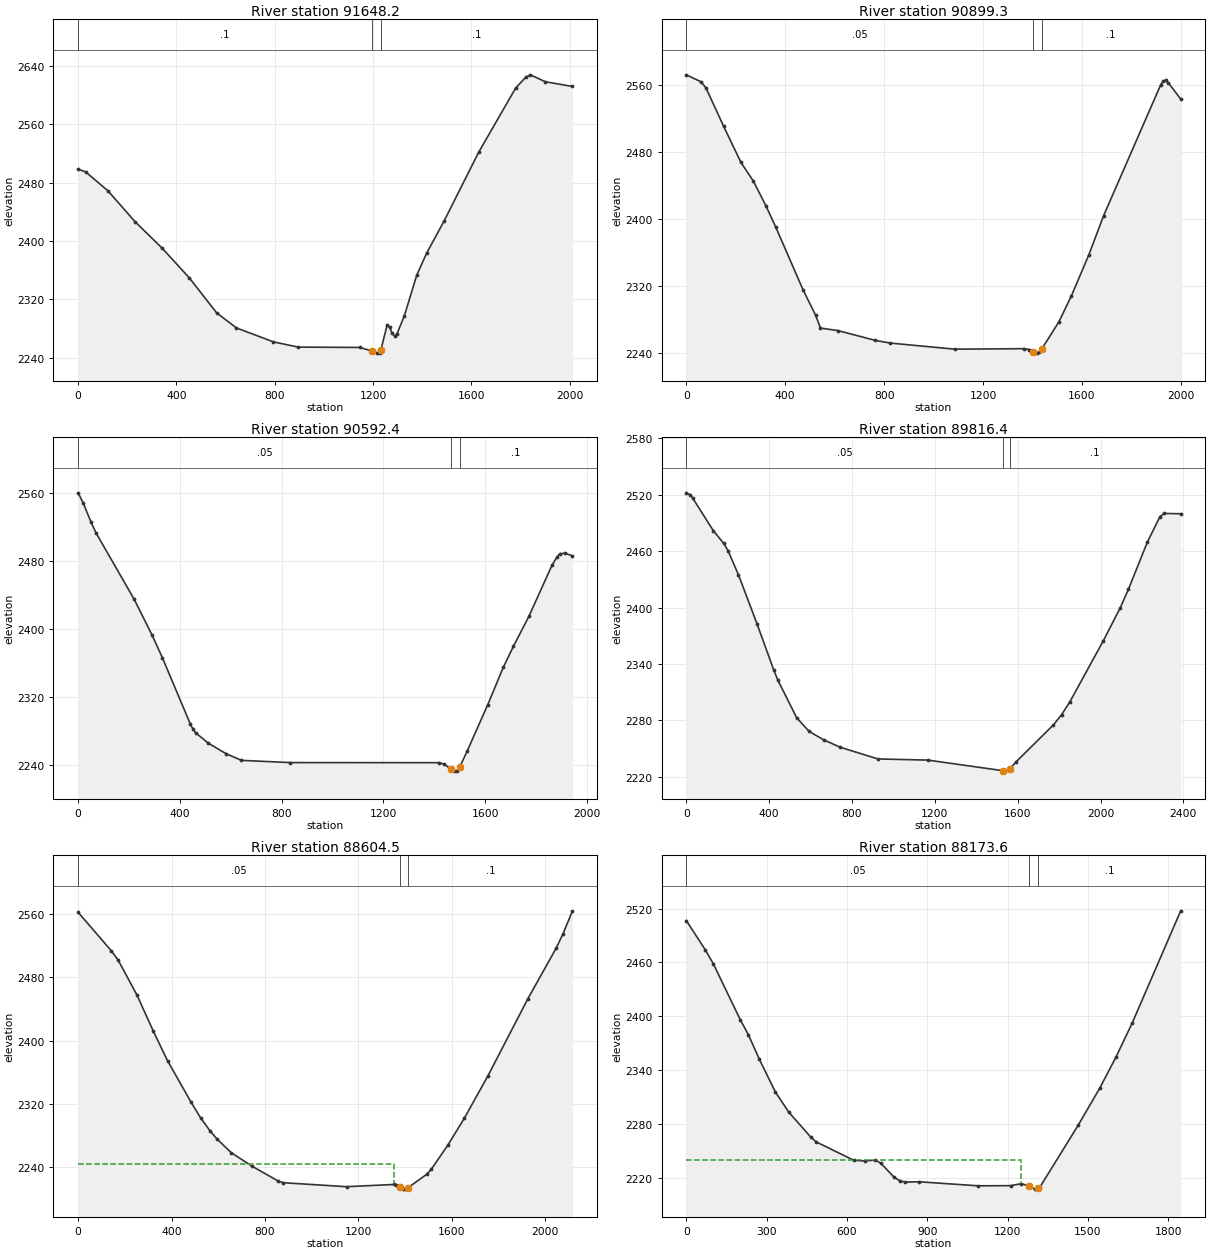
Type RM Length L Ch R = 1 ,91648.2 ,757.5,748.9,740.3
XS GIS Cut Line= 2
     2141384.312      395046.998     2141705.607       393061.56
#Sta/Elev= 30
       0 2498.49    30.2  2494.8   120.7 2468.97   231.3 2426.53   341.9  2390.1
   452.5 2349.28   563.2 2301.55   643.6  2280.8   794.4 2261.63     895 2254.46
  1146.4 2253.94  1196.7 2248.91  1216.8 2246.18  1226.9 2246.82 1231.75 2250.81
    1257 2284.47  1267.1    2282  1277.2 2273.49  1287.2 2269.58  1297.3 2272.59
  1327.4 2297.51  1377.7 2353.14  1417.9 2383.33  1488.3 2426.95  1629.1 2521.35
    1780 2609.61  1820.2 2624.27  1840.3  2627.8  1900.6 2618.34  2011.3 2611.82
#Mann= 3 , 0 , 0
       0      .1       0  1196.7    .045       0 1231.75      .1       0
Bank Sta=1196.7,1231.75
XS Rating Curve= 0 ,0
Exp/Cntr=0.3,0.1

Type RM Length L Ch R = 1 ,90899.3 ,308.9,306.9,304.9
XS GIS Cut Line= 2
     2142534.938      395312.973     2142209.524      393339.893
#Sta/Elev= 30
       0 2572.28    60.3 2563.82    80.4 2556.08   150.7  2510.9   221.1 2467.59
   271.3 2445.28   321.6 2416.05   361.8 2390.38   472.3  2315.4   522.5 2285.52
   542.6 2269.84     613 2266.84   763.7 2255.18     824 2251.95  1085.3 2244.66
  1366.6 2245.23  1386.8 2244.21  1404.2 2241.52  1416.9 2239.91    1427 2240.71
    1437 2244.57  1507.3 2277.39  1557.6 2308.35  1627.9 2357.11  1688.2 2404.27
  1919.3 2560.69  1929.4 2565.15  1939.4 2565.51  1949.5 2562.79  1999.7 2543.44
#Mann= 3 , 0 , 0
       0     .05       0  1404.2    .045       0    1437      .1       0
Bank Sta=1404.2,1437
XS Rating Curve= 0 ,0
Exp/Cntr=0.3,0.1

Type RM Length L Ch R = 1 ,90592.4 ,769.6,776.1,782.5
XS GIS Cut Line= 3
     2142694.655      395241.677     2142793.068      394637.781
     2142475.463      393344.995
#Sta/Elev= 30
       0 2560.69    20.1 2548.51    50.2 2526.52    70.2 2513.51   220.7 2435.02
   290.9 2392.94     331 2366.49   441.3 2288.11   451.4 2282.29   461.4 2278.12
   511.6  2265.7   581.8 2253.32   642.1 2245.48   833.7 2242.86  1418.7 2242.76
  1438.8 2240.96  1465.7 2235.01  1479.2  2232.8  1489.3 2233.41  1499.3  2237.2
  1529.6  2256.7  1610.3 2311.26  1670.8 2354.92  1711.1 2379.92  1771.6 2415.07
  1862.4 2475.29  1882.6 2485.22  1892.7 2488.81  1912.8 2489.57  1943.1 2486.48
#Mann= 3 , 0 , 0
       0     .05       0  1465.7    .045       0  1499.3      .1       0
Bank Sta=1465.7,1499.3
XS Rating Curve= 0 ,0
Exp/Cntr=0.3,0.1

Type RM Length L Ch R = 1 ,89816.4 ,1229,1211.9,1194.7
XS GIS Cut Line= 3
     2143585.384      395311.349     2143314.504      394114.961
     2143319.018      392954.691
#Sta/Elev= 30
       0 2522.02    20.1 2519.63    30.2 2516.59   130.7  2481.6     181 2468.14
   201.1 2460.58   251.4    2435   341.9 2382.28   422.3 2333.42   442.4 2322.53
   532.9 2282.63   593.2 2268.15   663.6  2259.2     744 2251.27     925 2238.91
  1166.3 2237.67  1526.7 2226.47  1539.4 2225.94  1560.5 2227.85  1589.9 2235.33
  1771.5 2274.92  1811.8 2285.92  1852.2 2299.83  2013.6 2364.71  2094.4 2399.39
  2134.7 2419.39  2225.5 2469.33  2286.1 2496.41  2306.2 2500.07    2387 2499.76
#Mann= 3 , 0 , 0
       0     .05       0  1526.7    .045       0  1560.5      .1       0
Bank Sta=1526.7,1560.5
XS Rating Curve= 0 ,0
Exp/Cntr=0.3,0.1

Type RM Length L Ch R = 1 ,88604.5 ,427.6,430.9,434.3
XS GIS Cut Line= 2
     2145223.373      394569.175     2144020.577      392826.768
#Sta/Elev= 30
       0 2562.03   141.2 2513.73   171.4 2501.63     252 2457.45   322.6  2411.5
   383.1 2374.38   483.9    2322   524.3 2302.44   564.6 2285.96   594.8 2275.63
   655.3 2258.38   746.1 2241.03     857 2222.46   877.1  2220.4  1149.4 2215.35
    1351 2218.13  1361.1 2218.01    1379 2214.69  1391.3 2212.34  1401.4 2212.27
  1413.3 2214.18  1492.2 2230.85  1512.3 2237.24  1582.9 2267.66  1653.5 2301.62
  1754.3    2355  1925.7 2452.62  2046.7 2516.44  2076.9 2535.11  2117.2 2563.91
#Mann= 3 , 0 , 0
       0     .05       0    1379    .045       0  1413.3      .1       0
#XS Ineff= 2 , 0
         1350.77 2244.62
Permanent Ineff=
       F       F
Bank Sta=1379,1413.3
XS Rating Curve= 0 ,0
Exp/Cntr=0.3,0.1

Type RM Length L Ch R = 1 ,88173.6 ,661.3,645.1,628.8
XS GIS Cut Line= 2
     2145360.746      394324.649     2144515.291      392682.946
#Sta/Elev= 30
       0 2506.52    70.6 2474.06   100.9 2458.37   201.8 2395.94   232.1 2379.23
   272.4 2352.28     333 2315.31   383.4 2292.85   464.2 2265.53   484.4 2260.05
   625.6 2239.49     666 2238.74   706.4 2239.81   726.5 2236.26     777 2220.37
   797.2 2216.73   817.4 2215.14   867.8 2215.57  1089.8 2211.05  1210.9 2211.21
  1251.3  2213.4  1280.9 2210.84  1301.7 2207.35  1315.3 2208.36  1321.9 2210.14
  1463.2  2278.3  1543.9  2319.7  1604.4 2354.19    1665 2392.12  1846.6 2517.43
#Mann= 3 , 0 , 0
       0     .05       0  1280.9    .045       0  1315.3      .1       0
#XS Ineff= 2 , 0
         1250.41 2239.63
Permanent Ineff=
       F       F
Bank Sta=1280.9,1315.3
XS Rating Curve= 0 ,0
Exp/Cntr=0.3,0.1

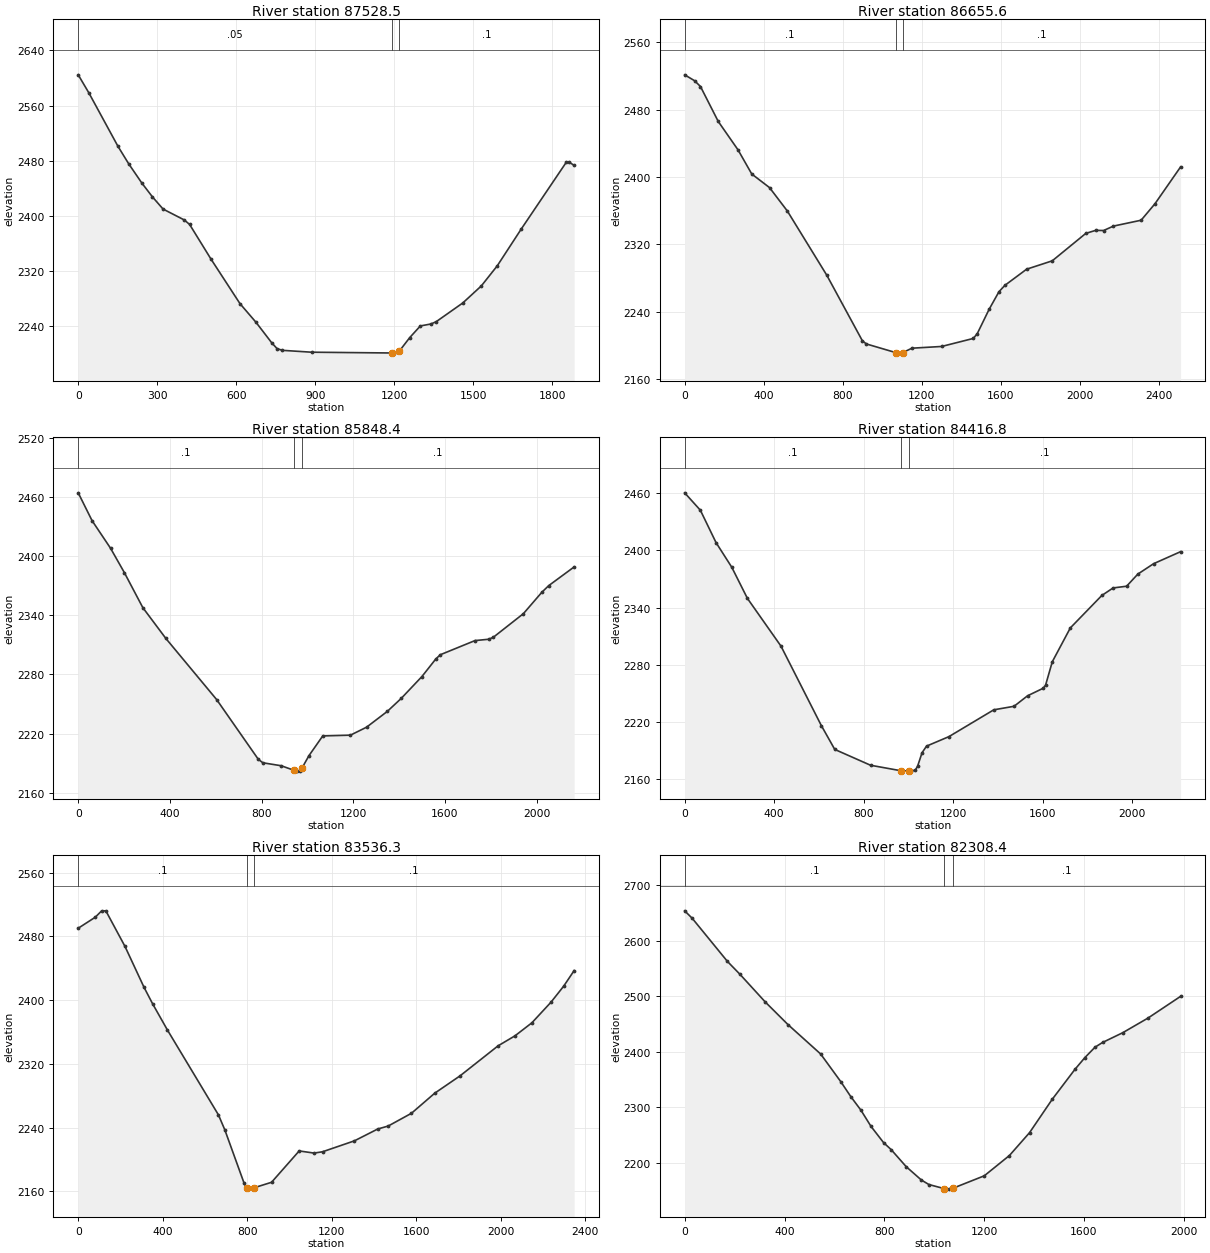
Type RM Length L Ch R = 1 ,87528.5 ,878.1,873,866.7
XS GIS Cut Line= 2
     2146306.713      393316.949     2144634.333      392451.924
#Sta/Elev= 30
       0 2604.69    40.3 2578.58     151 2500.86   191.3 2475.77   241.6  2447.6
   281.9 2427.49   322.2 2409.86   402.8 2394.02   422.9 2387.54   503.4 2337.66
   614.2 2272.56   674.6 2245.69     735 2215.58   755.2 2207.23   775.3 2204.82
     886 2202.11  1190.6 2200.97  1198.2 2200.77  1218.3  2203.3  1258.6  2223.3
  1298.9 2240.24  1339.1 2243.06  1359.3 2246.47    1460 2273.58  1530.4 2298.31
  1590.9  2327.5  1681.5 2380.64  1852.6  2477.6  1862.7 2478.29  1882.8 2473.22
#Mann= 3 , 0 , 0
       0     .05       0  1190.6    .045       0  1218.3      .1       0
Bank Sta=1190.6,1218.3
XS Rating Curve= 0 ,0
Exp/Cntr=0.3,0.1

Type RM Length L Ch R = 1 ,86655.6 ,791.3,807.1,823
XS GIS Cut Line= 4
     2146339.667      392979.177     2146141.947      392287.158
     2145441.689      391986.459     2144922.674      391096.719
#Sta/Elev= 30
       0  2521.4      50 2514.42      80 2507.53   169.9 2466.08   269.9  2432.4
   339.9 2403.61   429.8 2387.48   519.8 2359.76   719.7 2283.49   900.2 2205.54
   920.3 2201.84  1069.4 2191.56  1090.7 2190.95  1104.4 2191.58  1150.9 2196.81
  1301.3 2198.86  1461.8 2208.38  1481.8 2214.03  1541.8 2242.91  1591.8 2263.86
  1621.8 2271.43  1731.8 2290.59  1861.8 2300.55  2031.8 2333.15  2081.8 2336.72
  2121.8 2336.54  2171.8  2341.8  2311.8 2348.75  2381.8 2368.26  2511.9 2412.12
#Mann= 3 , 0 , 0
       0      .1       0  1069.4    .045       0  1104.4      .1       0
Bank Sta=1069.4,1104.4
XS Rating Curve= 0 ,0
Exp/Cntr=0.3,0.1

Type RM Length L Ch R = 1 ,85848.4 ,1411.9,1431.6,1442.1
XS GIS Cut Line= 3
     2146961.661      391945.267      2146520.91      391899.956
     2145503.476      390511.798
#Sta/Elev= 30
       0 2464.57    60.4 2436.32     141  2408.3   201.4 2383.51     282 2347.91
   382.6 2316.59   604.1 2254.53   785.3 2194.04   805.4 2190.32   885.9  2187.3
   940.3 2182.77   956.4 2181.83   966.4 2182.16   975.5  2184.5  1006.7 2197.47
  1067.1 2217.58  1187.9 2218.37  1258.3 2226.46  1348.9 2242.52  1409.3 2255.65
  1499.9 2277.92  1560.3 2295.73  1580.4  2300.1  1731.4 2314.45  1791.8 2315.82
  1811.9 2317.89  1942.7 2341.81  2023.3 2363.56  2053.4 2370.32  2164.2  2389.3
#Mann= 3 , 0 , 0
       0      .1       0   940.3    .045       0   975.5      .1       0
Bank Sta=940.3,975.5
XS Rating Curve= 0 ,0
Exp/Cntr=0.3,0.1

Type RM Length L Ch R = 1 ,84416.8 ,913.3,880.5,857
XS GIS Cut Line= 4
      2147307.67      391385.061     2147156.241      390824.437
     2146950.541      390144.485     2146088.398      389807.421
#Sta/Elev= 30
       0 2460.38    70.1 2442.13   140.2 2408.17   210.3 2382.41   280.4 2349.66
   430.5 2299.56   610.7  2216.3   670.8 2191.23   830.8 2174.63     965 2168.93
  1000.8 2168.61    1011 2168.46    1031 2169.65    1041 2173.54    1061 2187.73
    1081 2194.67    1181 2204.63  1381.7 2232.78  1472.2 2236.46  1532.6 2247.48
    1603 2255.45  1613.1 2258.58  1643.3 2283.23  1723.8 2318.67  1864.6 2352.72
  1914.9  2360.6  1975.3 2362.41  2025.6 2375.14    2096 2386.04  2216.8 2398.67
#Mann= 3 , 0 , 0
       0      .1       0     965    .045       0  1000.8      .1       0
Bank Sta=965,1000.8
XS Rating Curve= 0 ,0
Exp/Cntr=0.3,0.1

Type RM Length L Ch R = 1 ,83536.3 ,1228.2,1227.8,1227.5
XS GIS Cut Line= 3
     2148535.181      390421.176     2147340.624      389865.089
     2146850.443      388958.873
#Sta/Elev= 30
       0  2490.3    80.5 2504.07   110.6 2512.01   130.8 2512.14   221.3 2467.56
   311.8 2416.06     352 2395.58   422.4 2362.57   663.8 2256.14     694 2237.39
   784.6 2170.92   797.2 2164.44   804.7 2162.94   833.3 2164.72   915.3 2171.51
  1046.1 2210.86  1116.5 2208.17  1156.7 2209.81  1307.6 2223.52  1417.7 2238.34
  1467.7 2242.13  1577.7 2258.12  1687.8  2283.3  1807.8 2305.09  1987.8 2342.75
  2067.9 2355.31  2147.9 2371.66  2237.9 2397.39  2297.9 2417.45  2347.9  2437.2
#Mann= 3 , 0 , 0
       0      .1       0   797.2    .045       0   833.3      .1       0
Bank Sta=797.2,833.3
XS Rating Curve= 0 ,0
Exp/Cntr=0.3,0.1

Type RM Length L Ch R = 1 ,82308.4 ,902.7,901.7,900.8
XS GIS Cut Line= 2
     2149206.605      389457.292     2147398.292      388633.459
#Sta/Elev= 30
       0 2653.72    30.3 2640.21   171.5 2562.48   221.9 2539.18   322.8 2489.56
   413.6  2448.9   544.7 2395.86   625.4 2346.02   665.7 2318.95   706.1 2294.66
   746.4  2265.5   796.9 2236.18   827.1 2223.67   887.6 2192.82   948.2 2168.84
   978.4 2160.68  1038.6 2153.45  1059.1 2152.38    1075    2154  1200.4 2176.37
  1301.2 2212.94  1381.9 2254.15  1472.7 2314.21  1563.5 2368.04  1603.8 2389.47
  1644.2 2408.08  1674.4 2416.59  1755.1 2434.12    1856 2460.42  1987.1 2499.69
#Mann= 3 , 0 , 0
       0      .1       0  1038.6    .045       0    1075      .1       0
Bank Sta=1038.6,1075
XS Rating Curve= 0 ,0
Exp/Cntr=0.3,0.1

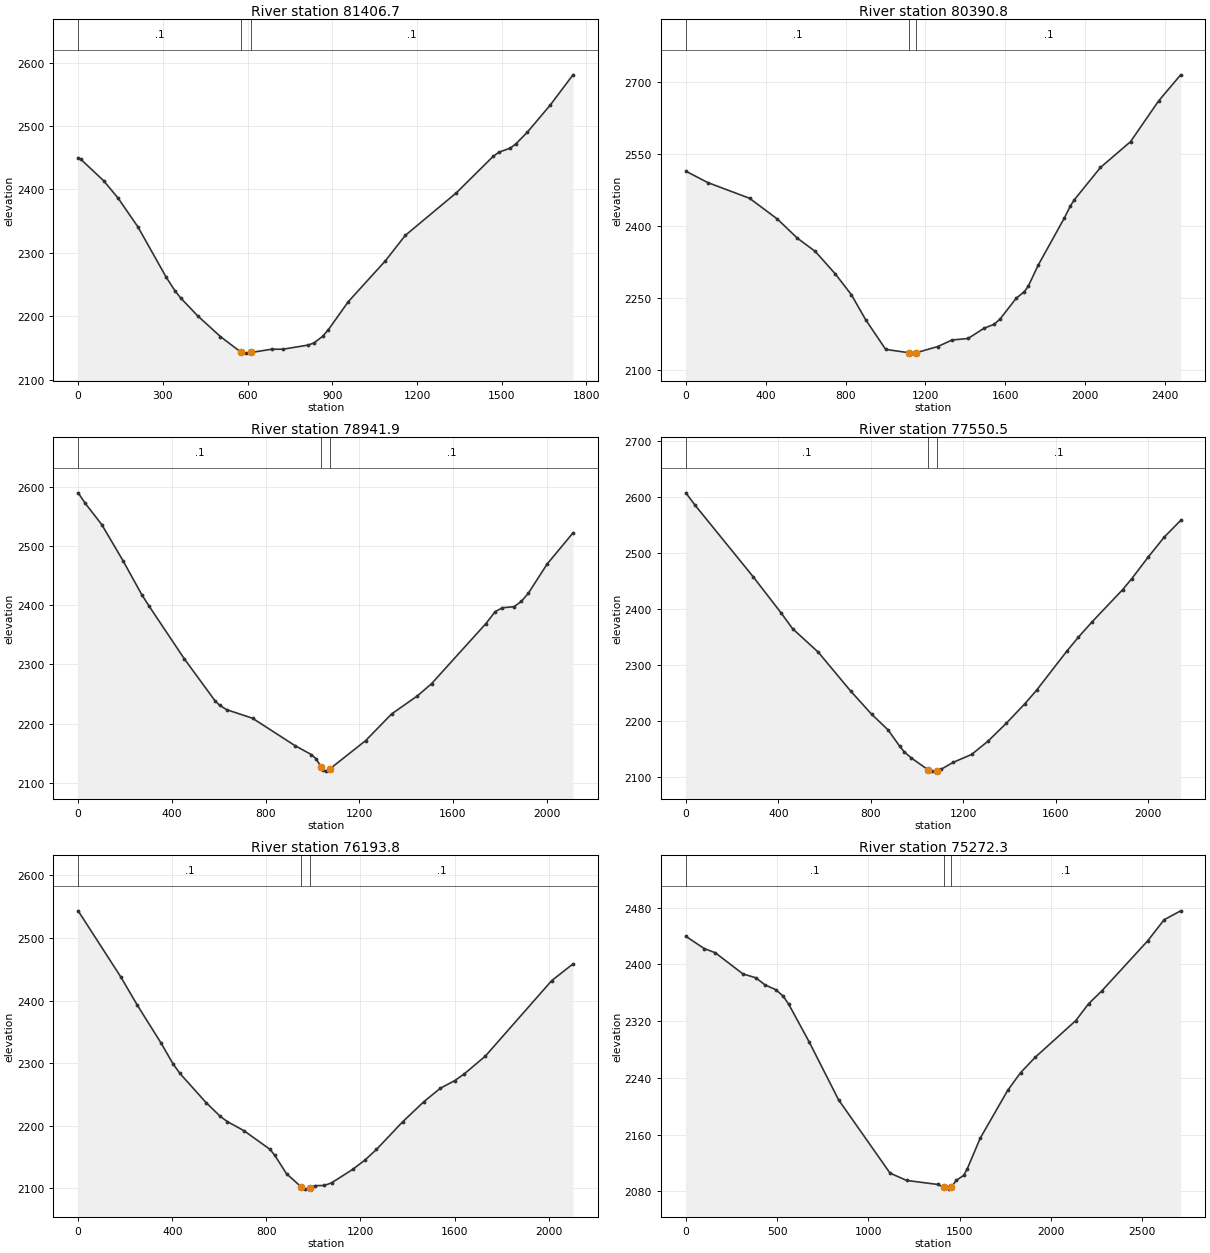
Type RM Length L Ch R = 1 ,81406.7 ,1007.6,1015.8,1024.1
XS GIS Cut Line= 2
     2149227.201      388448.096     2147591.893      387817.864
#Sta/Elev= 30
       0 2450.06    10.1  2447.3    90.6 2413.61     141 2386.66   211.5 2341.19
   312.2 2261.53   342.4 2240.79   362.6 2229.37     423  2201.1   503.6 2168.37
     577 2143.57   594.2  2142.2   613.7  2143.3   684.9 2148.35   725.2 2148.37
   815.8    2155     836 2158.49   866.2  2168.8   886.4 2179.23   956.8 2223.29
  1087.8 2287.43  1158.3 2327.54  1339.6 2394.79  1470.5 2452.48  1490.7 2458.79
    1531 2465.26  1551.1 2472.17  1591.4 2490.49    1672 2532.99  1752.6 2580.62
#Mann= 3 , 0 , 0
       0      .1       0     577    .045       0   613.7      .1       0
Bank Sta=577,613.7
XS Rating Curve= 0 ,0
Exp/Cntr=0.3,0.1

Type RM Length L Ch R = 1 ,80390.8 ,1435.3,1448.9,1462.5
XS GIS Cut Line= 4
     2149886.267      387636.621     2149243.678      387550.119
     2148646.399      387072.295     2148473.394      386021.909
#Sta/Elev= 30
       0 2513.86   109.7 2490.11   319.2  2457.3   458.9 2413.86   558.6 2374.08
   648.4 2346.36     749 2299.37   829.5  2255.8     900 2204.34  1000.6 2142.18
  1116.6 2135.22  1141.5 2134.36  1153.8 2135.21  1262.3 2148.18  1332.8 2161.73
  1413.3 2164.89  1493.6 2186.39  1543.8 2194.46    1574 2205.72  1654.3 2248.88
  1694.5 2262.25  1714.6 2273.86  1764.8 2318.22  1895.3  2416.2  1925.5 2441.25
  1945.6 2454.36  2076.1 2521.53  2226.7 2575.38  2367.3 2660.36  2477.8 2714.78
#Mann= 3 , 0 , 0
       0      .1       0  1116.6    .045       0  1153.8      .1       0
Bank Sta=1116.6,1153.8
XS Rating Curve= 0 ,0
Exp/Cntr=0.3,0.1

Type RM Length L Ch R = 1 ,78941.9 ,1386.3,1391.4,1396.6
XS GIS Cut Line= 2
     2150372.329      387434.782     2149585.568       385474.06
#Sta/Elev= 30
       0  2590.4    30.2 2572.72   100.6 2536.73   191.2 2475.82   271.6  2418.1
   301.8 2399.35   452.7 2309.88   583.5 2239.02   603.6 2231.06   633.8 2223.57
   744.5 2209.04   925.6 2162.75     996 2147.49  1016.1 2140.38  1037.2 2126.63
  1046.3 2121.56  1056.3 2119.56  1074.8 2123.38  1227.4  2171.2    1338 2216.18
  1448.7 2246.96  1509.1 2267.63  1740.4 2368.99  1780.7 2389.43  1810.9 2395.93
  1861.2 2397.74  1891.4 2406.55  1921.5 2420.16    2002 2469.78  2112.7 2522.67
#Mann= 3 , 0 , 0
       0      .1       0  1037.2    .045       0  1074.8      .1       0
Bank Sta=1037.2,1074.8
XS Rating Curve= 0 ,0
Exp/Cntr=0.3,0.1

Type RM Length L Ch R = 1 ,77550.5 ,1357.5,1356.7,1355.9
XS GIS Cut Line= 2
     2151447.431      387014.627      2151056.11      384909.734
#Sta/Elev= 30
       0 2607.58    40.2 2585.38   291.5 2457.52   412.1 2392.98   462.4 2364.52
   572.9 2322.82   713.6 2253.02   804.1 2211.75   874.5 2184.08   924.7 2155.02
   944.8 2144.72     975 2133.83  1048.7 2112.39  1065.4 2110.13  1086.8 2110.68
  1105.7 2113.72  1155.9 2125.66  1236.3 2139.91  1306.7 2163.41  1387.1 2195.93
  1467.5 2230.83  1517.8 2254.93  1648.4 2324.55  1698.7 2349.68    1759 2377.52
  1889.7 2434.41  1929.9 2454.44  2000.2 2492.59  2070.6 2528.81    2141  2558.3
#Mann= 3 , 0 , 0
       0      .1       0  1048.7    .045       0  1086.8      .1       0
Bank Sta=1048.7,1086.8
XS Rating Curve= 0 ,0
Exp/Cntr=0.3,0.1

Type RM Length L Ch R = 1 ,76193.8 ,917.4,921.5,925.7
XS GIS Cut Line= 2
     2152794.397      386816.907     2152345.014      384761.875
#Sta/Elev= 30
       0 2543.55   181.2    2438   251.6 2392.74   352.3 2332.42   402.6 2299.49
   432.8 2283.68   543.5 2237.32   603.9 2215.28   634.1  2206.9   704.6 2192.36
   815.3 2162.56   835.4 2153.29   885.7 2123.56   948.8 2102.39   966.2 2098.96
   987.4 2101.49  1006.5 2104.44  1046.8 2104.82    1077 2108.96  1167.5  2130.6
  1217.9 2145.02  1268.2 2162.35  1378.9  2206.3  1469.5 2238.62    1540 2260.21
  1600.3 2272.18  1640.6 2282.79  1731.2 2311.55    2013 2432.03  2103.6 2458.77
#Mann= 3 , 0 , 0
       0      .1       0   948.8    .045       0   987.4      .1       0
Bank Sta=948.8,987.4
XS Rating Curve= 0 ,0
Exp/Cntr=0.3,0.1

Type RM Length L Ch R = 1 ,75272.3 ,630.6,605.7,581.3
XS GIS Cut Line= 2
     2153408.153       386804.55     2153243.386      384098.259
#Sta/Elev= 30
       0 2439.55   100.8 2422.23   161.3 2416.33   312.4 2386.57     383 2381.08
   433.4 2371.15   493.9 2364.13   534.2 2354.91   564.4 2343.43   675.3 2290.88
   836.6 2209.15  1118.8  2105.7  1209.5 2095.37  1380.8 2089.69  1415.9 2085.53
  1441.3 2083.11  1454.8 2086.02  1481.6 2095.46    1522 2102.36  1542.1 2111.79
  1612.7 2154.78  1763.9  2222.5  1834.4 2247.36    1915 2269.14  2136.8 2320.72
  2207.3 2344.63  2277.9 2362.19  2529.9 2432.93  2620.6 2462.85  2711.3 2475.43
#Mann= 3 , 0 , 0
       0      .1       0  1415.9    .045       0  1454.8      .1       0
Bank Sta=1415.9,1454.8
XS Rating Curve= 0 ,0
Exp/Cntr=0.3,0.1

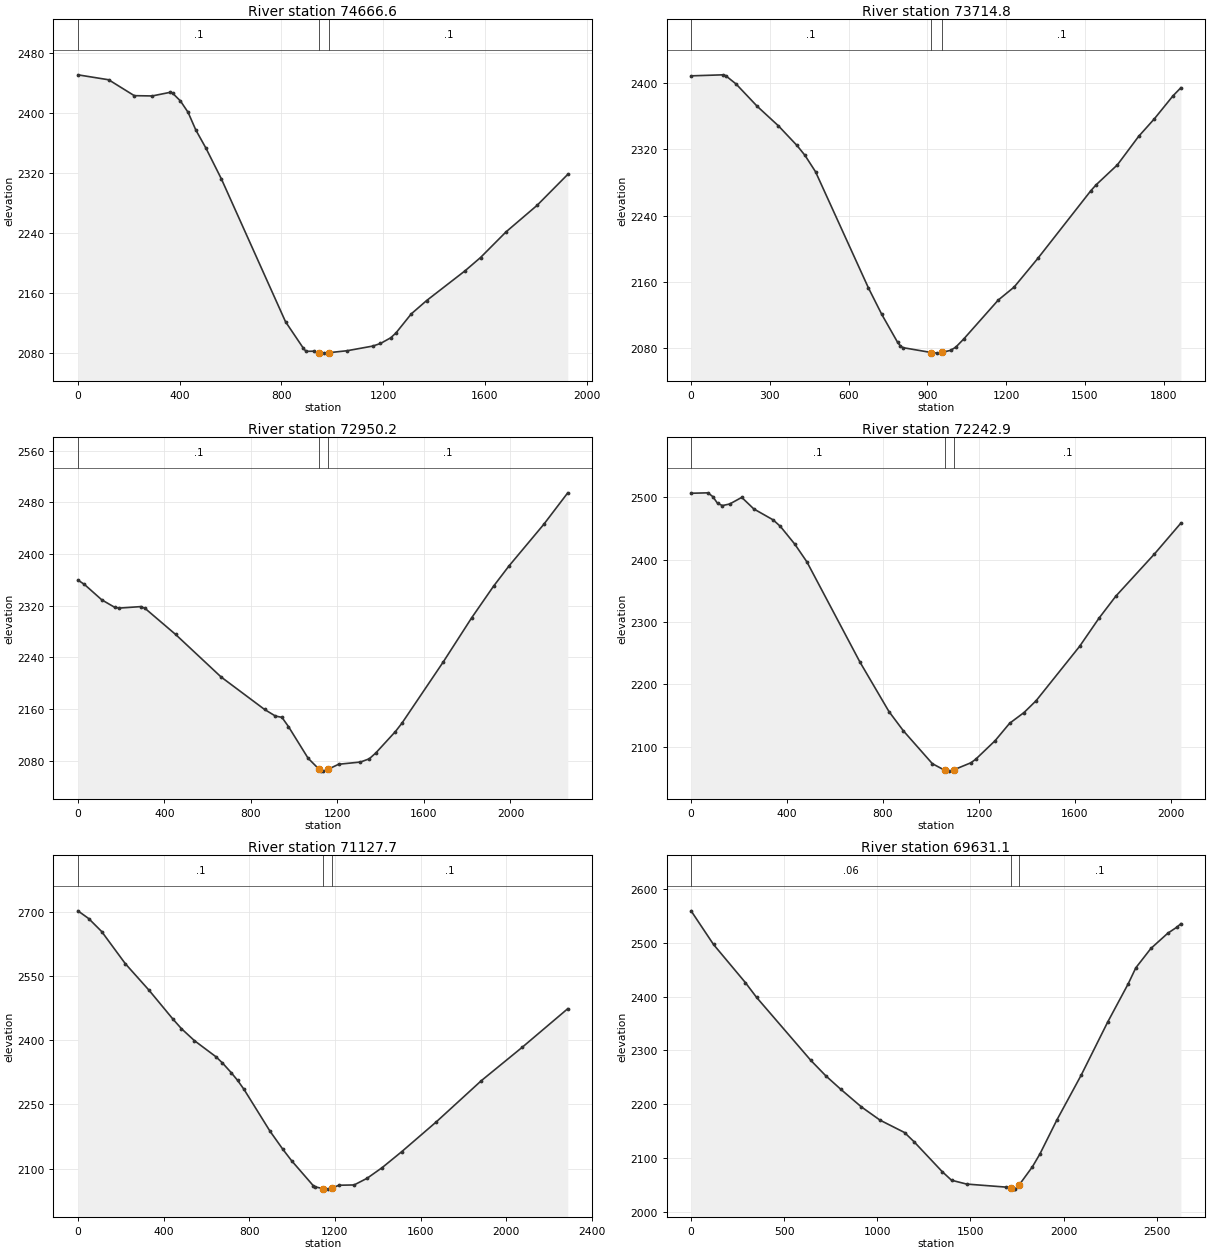
Type RM Length L Ch R = 1 ,74666.6 ,952.8,951.8,950.3
XS GIS Cut Line= 4
     2154734.524      385939.525     2154070.273      385579.336
     2153770.561      385279.624     2153426.117      384617.575
#Sta/Elev= 30
       0 2450.81   120.9 2444.23   221.6 2423.08   292.2  2422.7   362.7 2427.53
   372.8  2426.2     403 2416.07   433.2 2400.87   463.4 2377.46   503.8 2352.94
   564.2 2312.18   816.2 2122.18   886.8 2086.68   896.9 2082.75   927.2 2082.95
   948.9    2081   967.6 2080.38   988.1    2081  1058.4 2083.58  1159.3 2089.78
  1189.6 2093.23  1229.9 2100.82  1250.1 2107.12  1310.6 2132.62  1371.1  2150.4
  1522.4 2190.06  1582.9 2207.64  1683.7 2241.94  1804.8 2276.96  1925.8  2318.3
#Mann= 3 , 0 , 0
       0      .1       0   948.9    .045       0   988.1      .1       0
Bank Sta=948.9,988.1
XS Rating Curve= 0 ,0
Exp/Cntr=0.3,0.1

Type RM Length L Ch R = 1 ,73714.8 ,767.7,764.6,761.5
XS GIS Cut Line= 2
     2155206.385      385141.566     2153597.268      384197.927
#Sta/Elev= 30
       0 2409.22     121 2410.46   131.1 2409.61   171.4 2399.35   252.1 2372.25
   332.8 2348.61   403.3 2324.88   433.6 2312.96   473.9 2293.08   675.6 2152.15
     726 2120.32   786.5 2086.36   796.6 2082.24   806.7 2079.93   914.9    2074
   937.7 2073.28   954.3 2074.22   988.2  2076.6  1008.3  2080.6  1038.6  2090.5
  1169.7 2137.56  1230.2 2153.32  1320.9 2188.23  1522.6 2270.15  1542.7 2277.27
  1623.4 2301.37  1704.1 2335.78  1764.6  2357.3  1835.2 2385.01  1865.4 2394.88
#Mann= 3 , 0 , 0
       0      .1       0   914.9    .045       0   954.3      .1       0
Bank Sta=914.9,954.3
XS Rating Curve= 0 ,0
Exp/Cntr=0.3,0.1

Type RM Length L Ch R = 1 ,72950.2 ,708.9,707.3,705.6
XS GIS Cut Line= 3
     2155414.127      385064.103     2155076.106      384204.969
     2153847.262      383666.249
#Sta/Elev= 30
       0 2359.67    30.1 2352.88   110.4 2329.01   170.6 2317.35   190.7 2316.24
     291 2318.56   311.1 2315.63   451.6 2275.51   662.3 2209.57     863  2159.4
   913.2 2149.18   943.4 2147.15   973.7 2132.82  1064.5 2083.84  1115.5 2066.75
    1125 2064.45  1135.1 2063.93  1155.3 2066.59  1205.7 2074.56  1306.6 2078.01
    1347 2082.97  1377.2 2091.98    1468 2125.14  1498.3 2138.18    1690 2233.27
  1821.1 2301.44    1922  2350.2  1992.6  2381.2    2154 2445.82    2265 2494.64
#Mann= 3 , 0 , 0
       0      .1       0  1115.5    .045       0  1155.3      .1       0
Bank Sta=1115.5,1155.3
XS Rating Curve= 0 ,0
Exp/Cntr=0.3,0.1

Type RM Length L Ch R = 1 ,72242.9 ,1116,1115.2,1114.4
XS GIS Cut Line= 2
     2156125.377      383821.175     2154206.409      383124.009
#Sta/Elev= 30
       0 2506.32    70.4 2507.01    90.5 2500.95   110.6    2490   130.8  2486.6
   160.9 2489.08   211.2  2499.7   261.5 2481.17     342 2463.63   372.1  2453.2
   432.5 2424.58   482.8 2396.22     704 2235.42   824.7  2156.2   885.1 2125.13
  1005.8 2072.48  1056.4 2062.15  1076.2 2060.56  1096.4 2062.87  1166.7 2074.02
  1186.8 2079.79  1267.2 2109.38  1327.6 2137.26  1387.9 2154.61  1438.2 2173.55
  1619.3 2260.68  1699.7 2305.64  1770.1 2341.13    1931 2408.76  2041.7  2458.5
#Mann= 3 , 0 , 0
       0      .1       0  1056.4    .045       0  1096.4      .1       0
Bank Sta=1056.4,1096.4
XS Rating Curve= 0 ,0
Exp/Cntr=0.3,0.1

Type RM Length L Ch R = 1 ,71127.7 ,1498.1,1496.5,1495
XS GIS Cut Line= 2
     2156642.971      382785.989     2154470.487      382071.217
#Sta/Elev= 30
       0 2702.22    50.4 2684.12   110.8 2653.93   221.6  2578.6   332.5 2516.51
   443.3 2449.54   483.6 2426.86   544.1 2398.95   644.8 2361.25     675 2346.78
   715.3 2324.51   745.6 2306.15   775.8 2284.94   896.7 2187.61   957.1 2145.06
   997.4 2118.74  1098.2  2060.6  1108.3  2057.3  1146.1 2053.28  1168.7 2052.17
  1186.4 2054.94  1219.1 2061.26  1289.6 2061.92  1350.1 2077.49  1420.6 2102.45
  1511.3 2139.46  1672.5 2208.94    1884 2305.73  2075.5 2383.93    2287 2473.63
#Mann= 3 , 0 , 0
       0      .1       0  1146.1    .045       0  1186.4      .1       0
Bank Sta=1146.1,1186.4
XS Rating Curve= 0 ,0
Exp/Cntr=0.3,0.1

Type RM Length L Ch R = 1 ,69631.1 ,1103.1,1113,1122.8
XS GIS Cut Line= 3
     2157013.789      382033.724     2156412.864      381215.799
     2154852.129       380798.49
#Sta/Elev= 30
       0  2559.8   120.6 2497.17   291.4  2426.4   351.7 2398.82   643.1 2281.58
   723.5 2252.86   803.9 2227.83   914.4 2195.11  1014.9 2170.37  1146.2  2147.4
  1196.7 2130.51  1348.2 2074.75  1398.6 2058.63  1479.4  2051.5  1691.5 2045.84
    1719 2043.38  1731.8 2042.08    1742 2042.48  1759.9 2048.96  1832.8 2083.58
  1873.2 2107.44  1964.1 2170.56  2095.4 2254.44  2236.7 2352.53  2347.8 2424.31
  2388.2 2453.74    2469 2489.73  2559.8 2518.11  2610.3 2529.76  2630.5 2535.99
#Mann= 3 , 0 , 0
       0     .06       0    1719    .045       0  1759.9      .1       0
Bank Sta=1719,1759.9
XS Rating Curve= 0 ,0
Exp/Cntr=0.3,0.1

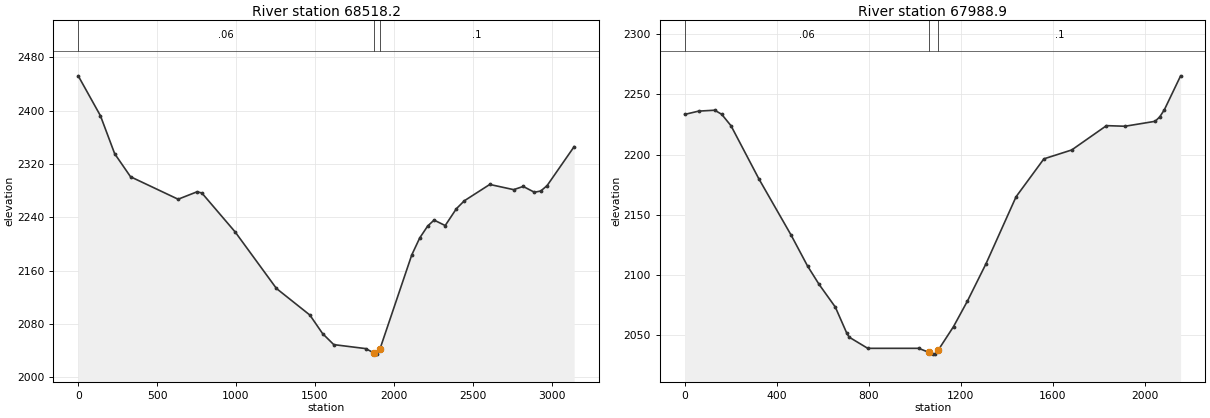
Type RM Length L Ch R = 1 ,68518.2 ,521.5,529.2,537
XS GIS Cut Line= 3
     2157279.823      381575.728     2156728.975      380423.956
     2155226.664      379316.001
#Sta/Elev= 30
       0 2452.34   140.7 2392.51   231.2 2335.41   331.8 2300.84   633.3 2267.12
     754 2278.36   784.1 2276.38   995.2  2217.9  1256.6 2133.14  1468.4 2093.26
  1549.2 2065.37  1619.8 2048.89  1821.6 2042.94  1871.9 2036.74  1892.2 2034.63
  1913.2 2042.79  2114.2 2183.57  2164.7 2209.06  2215.1  2226.9  2255.5 2235.81
  2326.1 2227.62  2396.7 2252.82  2447.2 2264.77  2608.6  2289.3    2760  2281.5
  2820.5 2286.31  2891.2 2277.62  2931.5 2279.42  2971.9 2287.56  3143.4 2346.09
#Mann= 3 , 0 , 0
       0     .06       0  1871.9    .045       0  1913.2      .1       0
Bank Sta=1871.9,1913.2
XS Rating Curve= 0 ,0
Exp/Cntr=0.3,0.1

Type RM Length L Ch R = 1 ,67988.9 ,848.7,839.8,830.9
XS GIS Cut Line= 2
     2157279.823      380580.446     2155990.339      378852.788
#Sta/Elev= 30
       0 2233.39    60.4 2236.14     131  2236.9   161.2 2233.44   201.5 2223.93
   322.4 2179.76   463.4 2132.59   533.9 2107.17   584.3 2091.78   654.8 2072.89
   705.2  2050.9   715.2 2047.81   795.8 2038.52  1017.5 2038.53  1061.9 2035.14
  1077.9 2033.69    1088 2033.92  1103.3 2037.37  1168.6 2056.62    1229 2077.88
  1309.6  2108.9  1440.6 2164.82  1561.5 2196.38  1682.4 2203.78  1833.5 2224.05
    1914 2223.54    2045 2227.66  2065.2 2231.36  2085.3 2237.36  2155.8 2265.55
#Mann= 3 , 0 , 0
       0     .06       0  1061.9    .045       0  1103.3      .1       0
Bank Sta=1061.9,1103.3
XS Rating Curve= 0 ,0
Exp/Cntr=0.3,0.1