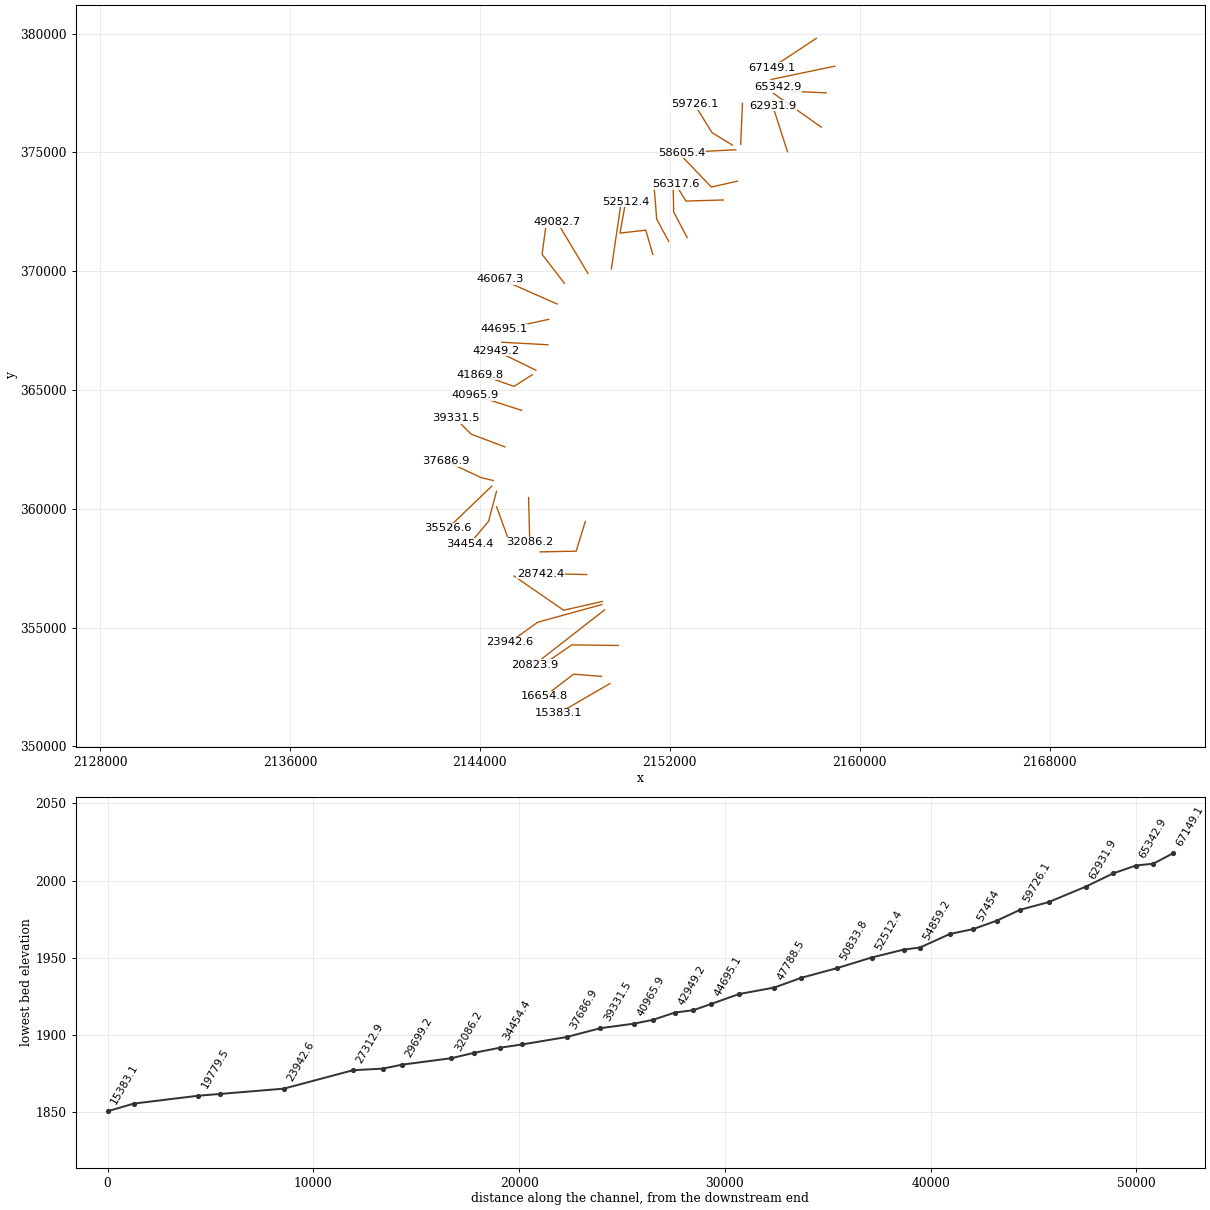
HEC-RAS study SpringCk.prj: SpringCk

--- SpringCk.g01 (geometry) --- (continued)

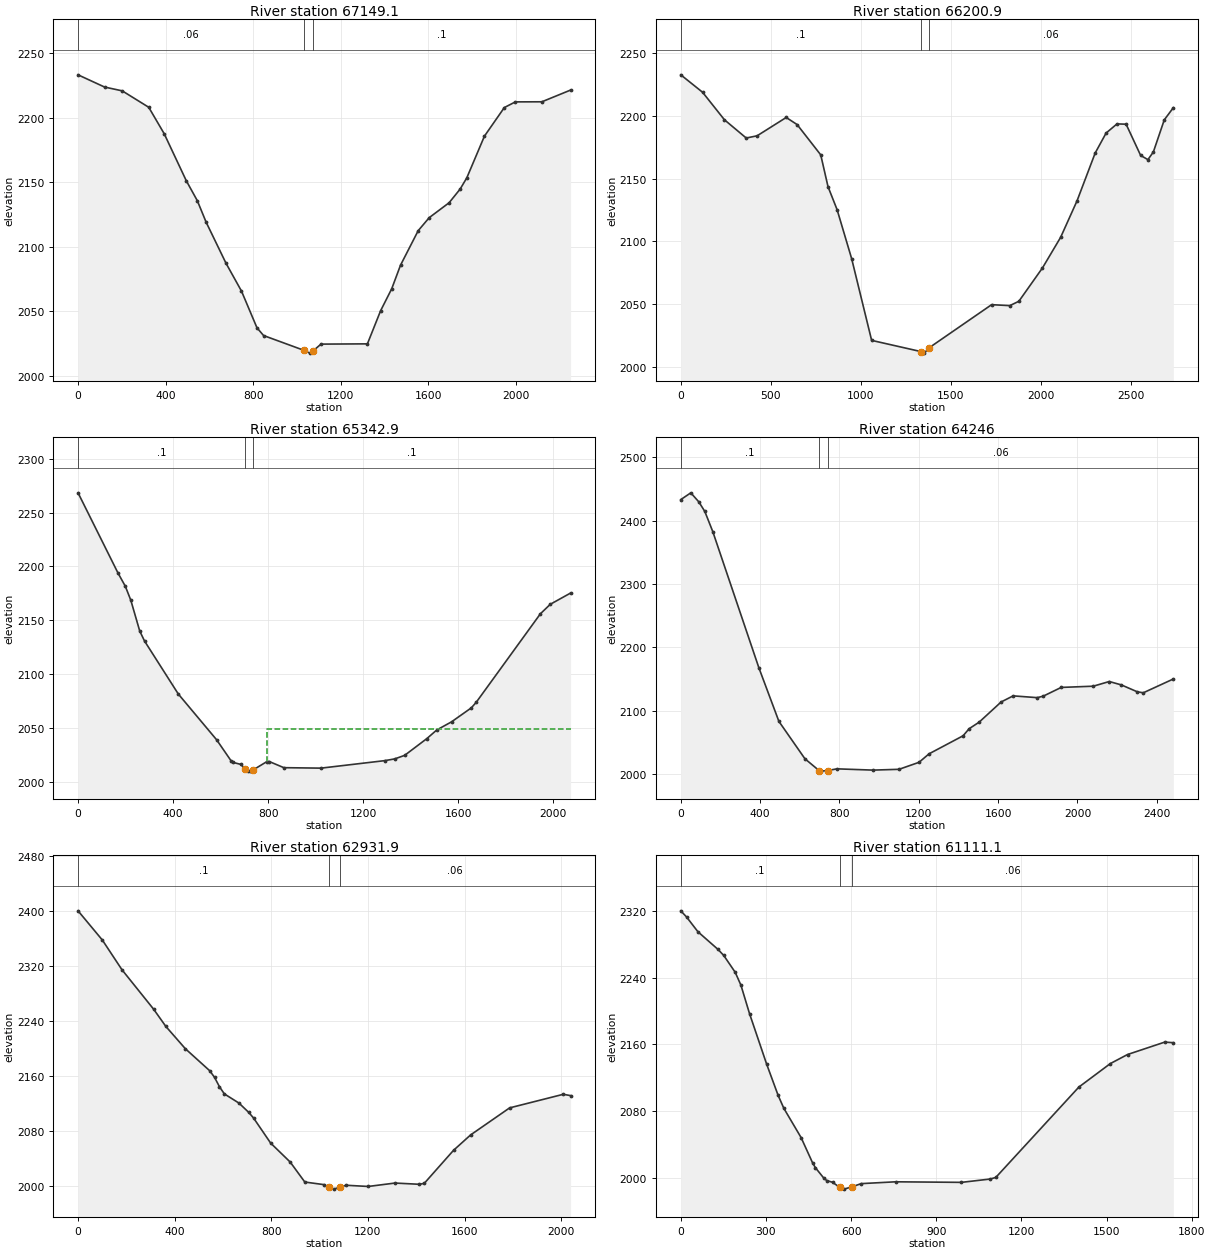
Type RM Length L Ch R = 1 ,67149.1 ,958.1,948.3,938.4
XS GIS Cut Line= 2
     2158168.691      379797.992     2156290.801      378558.585
#Sta/Elev= 30
       0 2233.36   121.1 2223.89   201.8 2220.93   322.9  2208.2   393.5 2187.69
   494.4 2151.25   544.8 2135.77   585.2 2119.06     676 2087.22   746.6 2065.66
   817.3 2037.21   847.5  2031.2  1030.3 2019.83  1059.4 2017.56  1072.1 2019.08
  1109.9 2024.55  1321.8 2024.75  1382.3  2050.5  1432.8 2067.45  1473.1 2085.77
  1553.8 2112.51  1604.3 2122.64  1695.1 2134.18  1745.5 2144.79  1775.8 2153.46
  1856.5 2185.84  1947.3 2207.99  1997.8 2212.38  2118.8 2212.45    2250 2221.55
#Mann= 3 , 0 , 0
       0     .06       0  1030.3    .045       0  1072.1      .1       0
Bank Sta=1030.3,1072.1
XS Rating Curve= 0 ,0
Exp/Cntr=0.3,0.1

Type RM Length L Ch R = 1 ,66200.9 ,864.9,857.9,851
XS GIS Cut Line= 2
     2158946.655      378626.798      2156268.56      378067.639
#Sta/Elev= 30
       0 2232.65   121.1 2218.75   242.3 2196.85   363.4  2182.3     424 2184.07
   585.5 2198.67   646.1 2193.02   777.3 2168.88   817.7 2143.54   868.2  2125.2
     949 2086.18    1060 2021.08  1334.9 2012.12  1352.8 2010.92    1377 2014.94
  1726.3 2049.52  1827.3 2048.77  1877.7 2052.22    2009 2078.84  2109.9 2103.23
  2200.8 2132.24  2301.7 2170.38  2362.3 2186.27  2422.9 2193.56  2473.4 2193.32
  2554.1 2168.45  2594.5 2165.07  2624.8  2171.2  2685.4 2196.78  2735.8 2206.48
#Mann= 3 , 0 , 0
       0      .1       0  1334.9    .045       0    1377     .06       0
Bank Sta=1334.9,1377
XS Rating Curve= 0 ,0
Exp/Cntr=0.3,0.1

Type RM Length L Ch R = 1 ,65342.9 ,1111.9,1096.9,1081.9
XS GIS Cut Line= 3
     2158582.859      377505.239     2157320.061      377556.188
     2156533.996      377745.426
#Sta/Elev= 30
       0 2268.43   168.6 2193.64   198.9 2181.57     222 2168.59   259.6  2139.9
   279.8 2130.64     422 2081.33     583 2038.85   643.6 2019.37   653.5 2017.72
     684    2016   703.2 2011.97   714.3 2009.98   724.4 2009.69   734.5 2010.53
   795.2 2018.63   805.3 2018.54   865.9  2012.9  1022.3 2012.47  1291.1 2019.46
  1332.4 2021.06  1374.2 2024.36  1467.7 2039.96  1509.2 2047.94  1571.5 2055.52
  1654.6  2068.5  1675.4 2073.71  1945.4    2156    1987 2164.81  2072.4 2175.27
#Mann= 3 , 0 , 0
       0      .1       0   703.2    .045       0   734.5      .1       0
#XS Ineff= 2 , 0
                          796.27         2048.65
Permanent Ineff=
       F       F
Bank Sta=703.2,734.5
XS Rating Curve= 0 ,0
Exp/Cntr=0.3,0.1

Type RM Length L Ch R = 1 ,64246   ,1331.1,1314.1,1297.2
XS GIS Cut Line= 2
     2158375.259      376060.992     2156347.138      377494.448
#Sta/Elev= 30
       0 2433.18    50.5 2443.86    90.9 2429.58   121.2 2414.42   161.5 2382.49
   393.7 2167.74   494.7  2083.1   625.9 2024.13     698 2005.31   706.7 2004.61
   740.7 2005.58   787.5 2008.21   969.2 2006.21  1100.4 2007.48  1201.4 2018.54
  1251.9 2031.95  1423.5 2060.42  1453.8 2071.53  1504.3 2081.89  1615.3 2113.78
  1675.9 2123.39    1797 2120.59  1827.3 2122.91  1918.2 2136.73  2079.7 2138.66
  2160.5 2146.04  2221.1 2140.74  2301.8  2129.8  2332.1 2128.27  2483.6 2150.05
#Mann= 3 , 0 , 0
       0      .1       0     698    .045       0   740.7     .06       0
Bank Sta=698,740.7
XS Rating Curve= 0 ,0
Exp/Cntr=0.3,0.1

Type RM Length L Ch R = 1 ,62931.9 ,1829.2,1820.8,1812.4
XS GIS Cut Line= 2
     2156954.322      375028.153     2156328.359      376968.639
#Sta/Elev= 30
       0 2400.18   100.9 2357.62   181.7 2314.71   312.9 2257.35   363.4 2232.39
   444.1 2200.02   545.1 2168.01   565.2 2158.34   585.4 2144.81   605.6 2134.42
   666.2 2121.04   706.6 2107.56   726.8 2099.26   797.4 2062.96   878.2 2035.46
   938.7 2006.44  1019.5 2002.59  1039.2 1998.81  1059.8 1996.14  1082.4 1999.03
  1110.3 2001.74  1201.2 2000.01  1312.2 2004.96  1413.1 2003.16  1433.3 2004.55
  1554.4  2052.5  1625.1 2074.83  1786.6  2114.1  2008.7 2133.81    2039  2131.9
#Mann= 3 , 0 , 0
       0      .1       0  1039.2    .045       0  1082.4     .06       0
Bank Sta=1039.2,1082.4
XS Rating Curve= 0 ,0
Exp/Cntr=0.3,0.1

Type RM Length L Ch R = 1 ,61111.1 ,1370.5,1385,1399.5
XS GIS Cut Line= 2
     2154982.538      375334.875     2155057.654      377068.793
#Sta/Elev= 30
       0 2320.68    20.2 2313.32    60.5 2295.46   131.2 2274.27   151.4    2267
   191.7 2246.78   211.9 2231.26   242.2 2197.04   302.7 2136.14   343.1 2098.66
   363.2 2083.12   423.8 2048.07   464.2 2017.74   474.2 2011.84   504.5    1999
   514.6 1996.29   534.8 1994.24   559.5 1988.25   575.2 1986.02   603.3 1988.83
   635.7 1992.63   756.8 1994.83   988.9 1994.16  1089.8 1998.14  1109.9 2000.08
  1402.6 2108.75  1513.6 2137.02  1574.1 2147.89  1705.3 2162.84  1735.5 2162.08
#Mann= 3 , 0 , 0
       0      .1       0   559.5    .045       0   603.3     .06       0
Bank Sta=559.5,603.3
XS Rating Curve= 0 ,0
Exp/Cntr=0.3,0.1

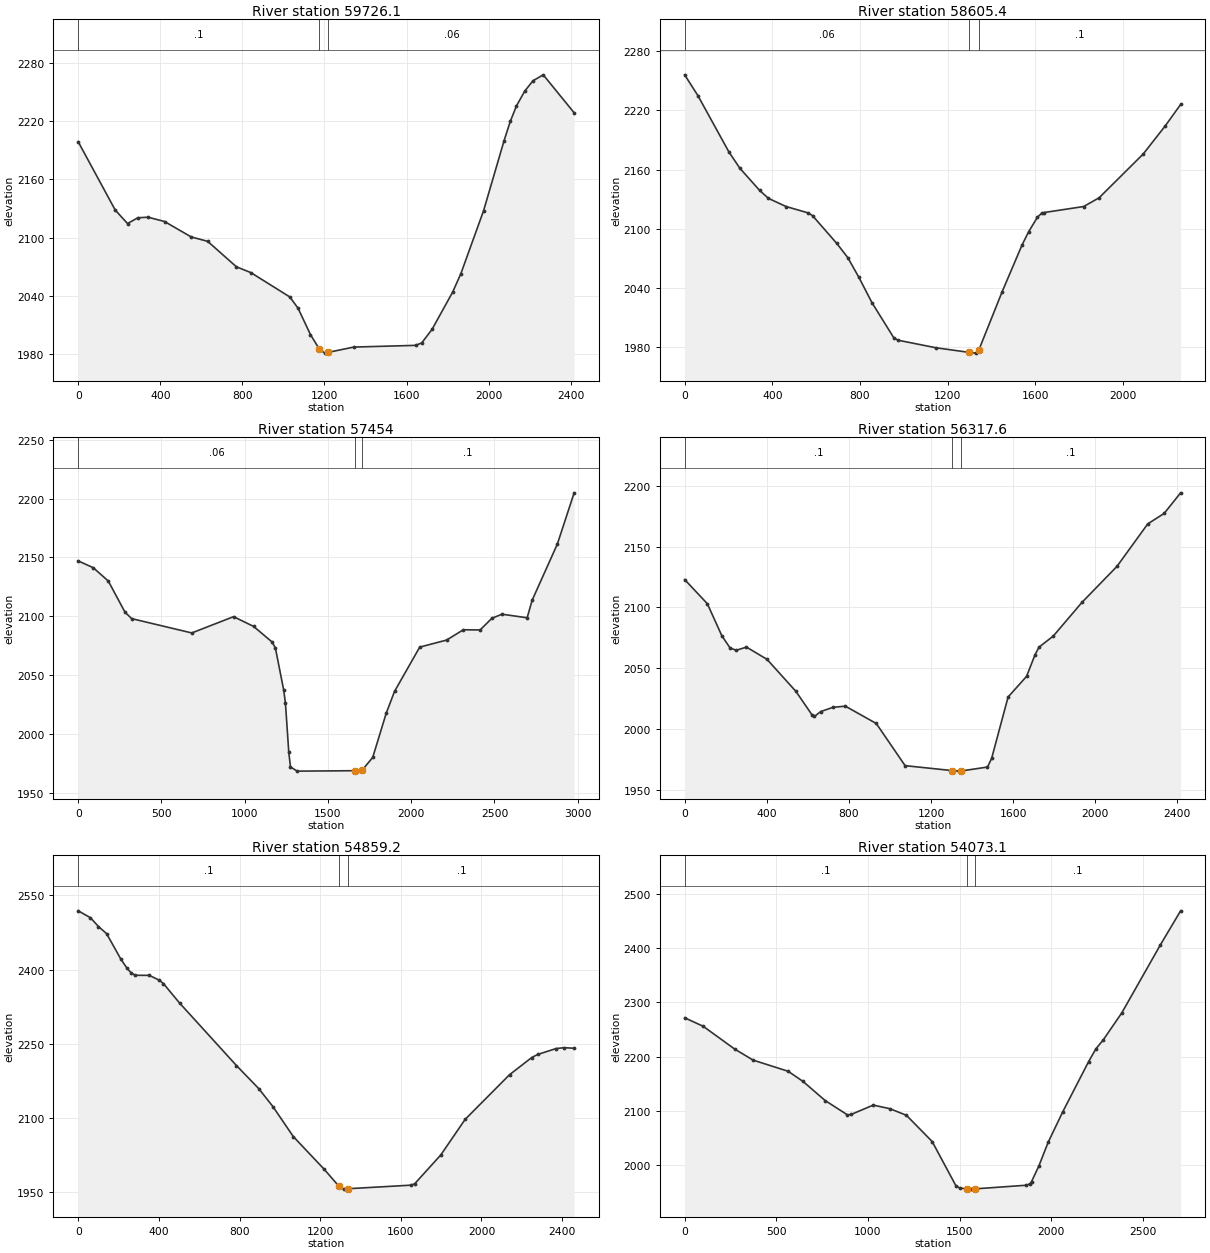
Type RM Length L Ch R = 1 ,59726.1 ,1092.5,1120.7,1148.8
XS GIS Cut Line= 3
     2154638.258      375303.576     2153774.429      375829.386
     2153035.792      377024.975
#Sta/Elev= 30
       0 2198.62   180.2  2128.4   240.3 2114.44   290.4 2120.41   340.4 2120.98
   420.5 2116.56   550.7 2100.67   630.8 2096.16     771 2069.91   841.1 2063.98
  1031.4 2038.86  1071.5  2027.2  1131.7 2000.16  1175.2 1985.15    1202 1981.08
  1219.5 1981.92  1342.5 1987.31  1643.7 1989.07  1673.8 1991.59    1724 2005.49
  1824.4 2043.82  1864.5 2062.84    1975 2127.49  2075.3 2199.89  2105.4 2219.62
  2135.6 2235.59  2175.7 2250.72  2215.9 2261.42    2266 2267.53  2416.6 2228.45
#Mann= 3 , 0 , 0
       0      .1       0  1175.2    .045       0  1219.5     .06       0
Bank Sta=1175.2,1219.5
XS Rating Curve= 0 ,0
Exp/Cntr=0.3,0.1

Type RM Length L Ch R = 1 ,58605.4 ,1173.9,1151.4,1128.9
XS GIS Cut Line= 2
      2154775.97      375109.528     2152516.243      374990.595
#Sta/Elev= 30
       0 2255.87    60.3 2234.83   201.1 2178.08   251.4 2161.39   341.9 2138.86
   382.2 2130.78   462.6 2122.53   563.2 2116.08   583.3  2113.3   693.9  2085.2
   744.2 2070.79   794.5 2050.97   854.9 2025.05   955.4 1989.18   975.5 1987.08
  1146.5 1979.52  1297.1 1974.87  1327.5 1974.09  1341.8 1977.09  1448.2 2036.09
  1538.7 2083.28  1568.9 2096.81  1609.1 2111.57  1629.3 2115.88  1639.3 2116.42
  1820.3 2122.52  1890.7 2131.34  2091.9 2175.64  2192.4  2204.1  2262.8 2225.83
#Mann= 3 , 0 , 0
       0     .06       0  1297.1    .045       0  1341.8      .1       0
Bank Sta=1297.1,1341.8
XS Rating Curve= 0 ,0
Exp/Cntr=0.3,0.1

Type RM Length L Ch R = 1 ,57454   ,1104.3,1136.4,1170.8
XS GIS Cut Line= 3
     2154844.826      373788.745      2153749.39       373538.36
     2152466.166      374877.921
#Sta/Elev= 30
       0 2147.07    90.3 2141.33   180.6 2130.01   280.9 2103.58     321 2098.08
   682.2 2085.92   933.1 2099.75  1053.5 2091.47    1164 2078.27  1184.2 2073.23
  1234.6 2037.14  1244.7 2026.25  1264.8 1984.46  1274.9 1972.16  1315.2  1968.6
  1660.6 1968.96  1705.6 1969.45  1768.9 1980.24  1849.6  2017.6    1900 2036.34
  2051.2 2073.89  2212.5 2079.87  2313.3 2088.63  2414.1 2088.47  2484.7 2098.39
  2545.2 2101.83  2696.4  2098.8  2726.7 2113.79  2877.9 2161.41  2978.7 2204.89
#Mann= 3 , 0 , 0
       0     .06       0  1660.6    .045       0  1705.6      .1       0
Bank Sta=1660.6,1705.6
XS Rating Curve= 0 ,0
Exp/Cntr=0.3,0.1

Type RM Length L Ch R = 1 ,56317.6 ,1511,1458.4,1403.4
XS GIS Cut Line= 3
     2154248.797      372995.121      2152673.78      372949.247
     2152237.974      373667.944
#Sta/Elev= 30
       0 2122.82   110.4 2103.02   180.6 2076.83   220.8 2066.72   250.9 2064.72
   301.1 2067.36   401.4 2057.26     542 2030.96   622.2 2011.22   632.3 2010.33
   662.4 2014.37   722.6 2017.86   782.8 2018.83   933.4 2004.59  1073.9 1969.94
  1301.9  1965.9  1334.8 1965.44  1347.4 1965.57  1475.3 1968.79  1495.4 1975.85
  1575.7 2026.37  1665.7  2043.3  1705.8 2060.63  1725.8 2067.25  1795.8 2076.42
  1935.9 2104.16    2106 2133.66  2256.1  2168.6  2336.1 2177.22  2416.2 2194.12
#Mann= 3 , 0 , 0
       0      .1       0  1301.9    .045       0  1347.4      .1       0
Bank Sta=1301.9,1347.4
XS Rating Curve= 0 ,0
Exp/Cntr=0.3,0.1

Type RM Length L Ch R = 1 ,54859.2 ,785.3,786.2,787
XS GIS Cut Line= 3
       2152727.3      371412.459     2152161.517      372490.504
     2152134.405      373732.409
#Sta/Elev= 30
       0  2518.5    60.4 2504.67   100.6 2486.79   140.9 2472.38   211.3 2421.13
   241.5 2402.87   261.6 2393.64   281.7 2388.32   352.2 2388.23   402.5 2378.44
   422.6 2371.67   503.1  2332.2   784.8 2206.16   895.5 2159.55     966  2123.1
  1066.6 2062.87  1217.5  1997.8  1293.8 1962.17  1317.7 1956.64  1339.8 1957.48
  1648.3  1964.6  1668.3 1967.23  1798.5 2025.75  1918.7 2097.32  2139.1 2187.58
  2249.3 2222.33  2279.4  2228.6  2369.5 2240.37  2409.6 2242.21  2459.7 2241.07
#Mann= 3 , 0 , 0
       0      .1       0  1293.8    .045       0  1339.8      .1       0
Bank Sta=1293.8,1339.8
XS Rating Curve= 0 ,0
Exp/Cntr=0.3,0.1

Type RM Length L Ch R = 1 ,54073.1 ,1513.5,1560.7,1607.2
XS GIS Cut Line= 3
     2151952.876      371247.335     2151445.794      372188.563
     2151314.394      373820.044
#Sta/Elev= 30
       0 2271.73   100.9 2256.08   272.3  2214.1   373.2 2193.59   564.8 2172.94
   645.5 2154.25   766.6  2118.9   887.6 2092.57   907.8 2093.17  1028.8  2110.5
  1119.3 2103.89  1209.7 2091.73  1350.3 2043.23  1480.8 1960.98  1500.9 1957.39
  1539.9 1955.75  1561.2 1955.33  1586.2 1955.88  1862.4 1962.48  1882.5 1964.84
  1892.5  1969.2  1932.7 1998.29  1982.9  2041.6  2063.2 2098.38  2203.8 2190.76
    2244 2214.54  2284.2 2231.16  2384.6 2280.62  2595.4 2406.35  2705.9 2469.26
#Mann= 3 , 0 , 0
       0      .1       0  1539.9    .045       0  1586.2      .1       0
Bank Sta=1539.9,1586.2
XS Rating Curve= 0 ,0
Exp/Cntr=0.3,0.1

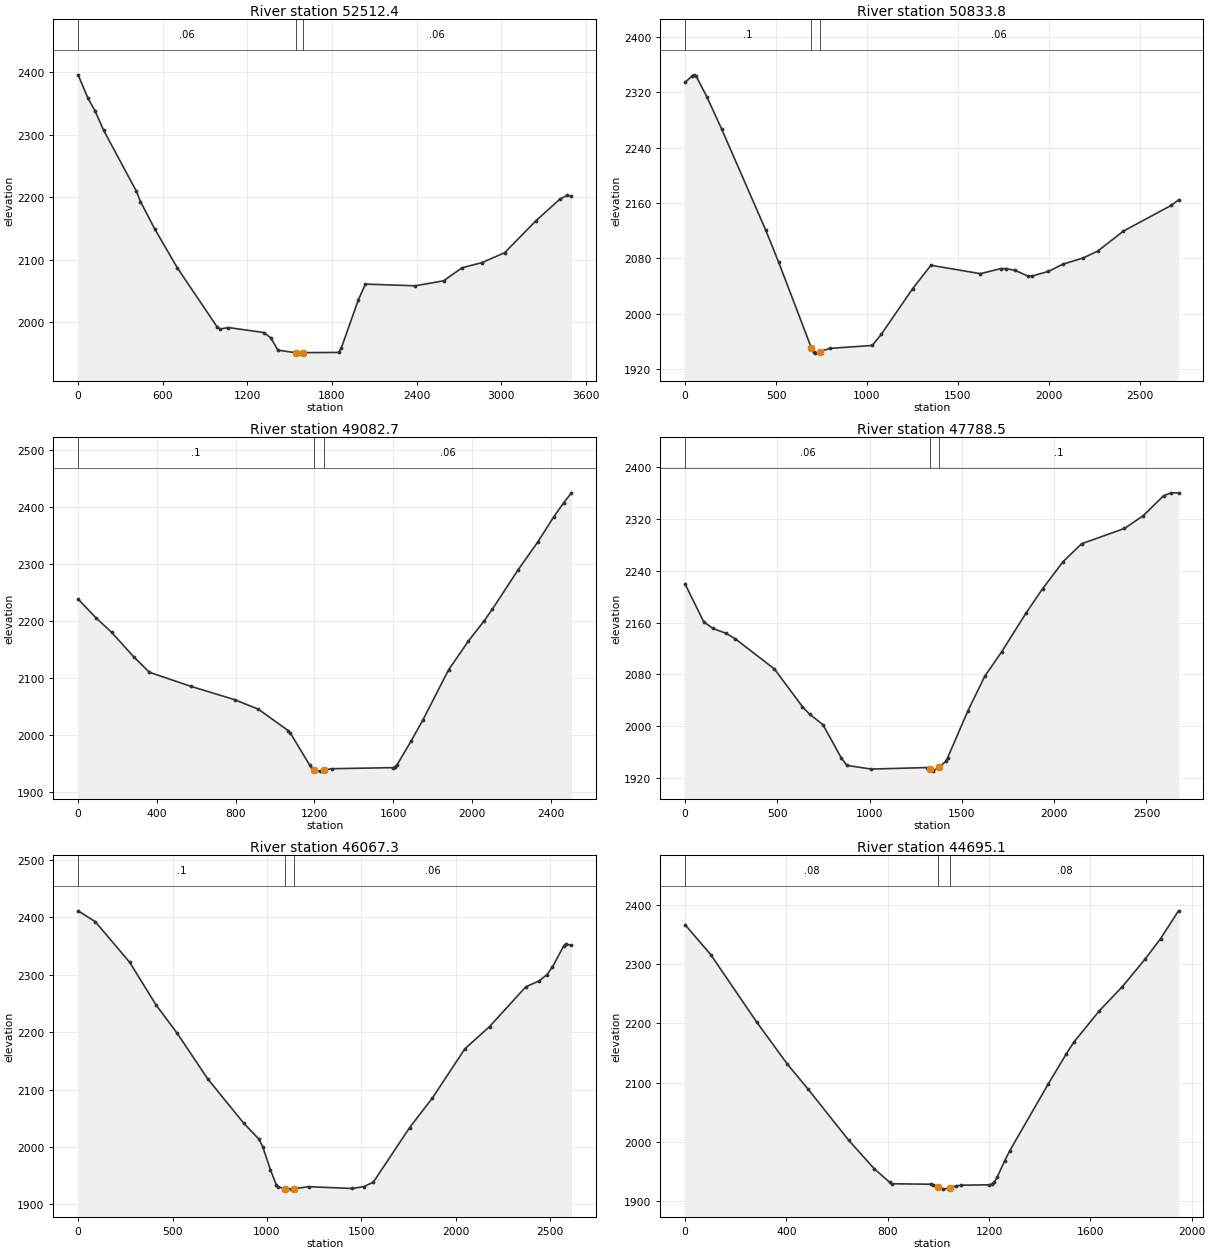
Type RM Length L Ch R = 1 ,52512.4 ,1731.5,1678.6,1626.3
XS GIS Cut Line= 4
     2151283.095      370702.747     2150984.077      371725.933
     2149898.887      371599.589     2150137.583      372918.657
#Sta/Elev= 30
       0  2395.6    70.4 2358.07   120.7 2337.74     181 2306.92   412.3 2209.81
   442.5 2192.78     543 2149.19     704 2086.64   985.5 1992.32  1005.6 1988.76
    1066 1991.14  1316.6 1983.18  1366.7 1974.65  1416.8    1955  1548.6 1950.72
  1577.2  1950.2  1595.4 1950.96  1847.8 1951.33  1867.8 1959.15  1988.1 2035.86
  2038.2 2060.65  2390.3 2057.96  2591.9 2065.89  2722.9 2086.82    2864 2095.06
  3025.3 2110.93    3247 2162.11  3418.4 2196.95  3468.8 2202.62    3499 2201.13
#Mann= 3 , 0 , 0
       0     .06       0  1548.6    .045       0  1595.4     .06       0
Bank Sta=1548.6,1595.4
XS Rating Curve= 0 ,0
Exp/Cntr=0.3,0.1

Type RM Length L Ch R = 1 ,50833.8 ,1732.6,1751.1,1769.6
XS GIS Cut Line= 2
     2149536.658      370095.562     2149931.015      372780.945
#Sta/Elev= 30
       0 2334.54    40.4    2344    50.4 2345.19    60.5 2343.46   121.1 2312.62
   201.8 2266.45     444 2120.61   514.6 2074.58   694.1 1951.25   706.3 1944.36
   716.4 1943.34   741.5 1945.59   797.1 1950.18  1029.2 1954.43  1079.6 1970.64
  1251.2 2036.28    1352 2070.17  1624.5 2058.07  1735.5  2065.3  1765.7  2065.4
  1816.2  2062.8  1886.8 2054.47    1907 2054.61  1997.8  2061.3  2078.5 2071.82
  2189.5 2080.74  2270.2 2090.78  2411.5 2119.59  2673.8 2156.65  2714.2 2164.47
#Mann= 3 , 0 , 0
       0      .1       0   694.1    .045       0   741.5     .06       0
Bank Sta=694.1,741.5
XS Rating Curve= 0 ,0
Exp/Cntr=0.3,0.1

Type RM Length L Ch R = 1 ,49082.7 ,1291.4,1294.2,1297
XS GIS Cut Line= 2
      2148552.74      369898.607     2147264.412      372048.568
#Sta/Elev= 30
       0 2238.27    90.6 2205.52   171.1 2179.88   281.8 2137.48   362.4 2110.09
   573.8  2085.4   795.2 2062.18     916 2045.45    1067 2008.08    1077 2004.45
  1177.7 1946.93  1187.8    1942  1199.7  1938.9    1228 1937.03  1247.7 1938.74
  1288.4 1941.27  1600.5 1943.15  1610.6 1944.48  1620.6  1948.3  1691.1  1989.4
  1751.5 2026.59  1882.3 2114.53    1983 2164.88  2063.5 2200.55  2103.8 2220.23
  2234.6 2289.17  2335.3  2338.3  2415.8 2381.97  2466.2  2406.7  2506.4 2424.33
#Mann= 3 , 0 , 0
       0      .1       0  1199.7    .045       0  1247.7     .06       0
Bank Sta=1199.7,1247.7
XS Rating Curve= 0 ,0
Exp/Cntr=0.3,0.1

Type RM Length L Ch R = 1 ,47788.5 ,1708,1721.2,1734.5
XS GIS Cut Line= 3
     2147558.797      369485.739     2146618.374      370709.053
     2146769.901      371829.481
#Sta/Elev= 30
       0 2219.59   100.8 2161.28   151.3 2150.97   221.9 2143.53   272.3 2134.92
   484.1 2088.46   635.4  2030.4   675.7 2018.33   746.3 2002.72   847.2 1950.77
   877.4 1939.56  1008.5 1933.97  1311.1 1936.26  1326.3  1933.6  1341.3 1930.77
  1374.7  1936.4  1411.9 1945.76    1422 1951.14  1532.9 2024.24  1623.8 2077.27
  1714.6 2114.68  1845.9 2174.15  1936.7 2212.19  2047.8  2254.1  2148.7  2281.8
  2380.9 2305.42  2481.8 2324.97  2592.9 2355.93  2633.3 2360.41  2673.6 2360.39
#Mann= 3 , 0 , 0
       0     .06       0  1326.3    .045       0  1374.7      .1       0
Bank Sta=1326.3,1374.7
XS Rating Curve= 0 ,0
Exp/Cntr=0.3,0.1

Type RM Length L Ch R = 1 ,46067.3 ,1355.3,1372.2,1389.2
XS GIS Cut Line= 2
     2147251.892      368618.289     2144860.713      369669.907
#Sta/Elev= 30
       0 2411.53    90.8 2392.69   272.3 2322.23   413.5  2247.2   524.5 2198.24
   685.8 2118.98   877.5 2041.22   958.2 2013.48   978.3 1999.79  1018.7 1960.01
  1048.9 1934.45    1059  1930.4  1093.5 1927.48  1129.6 1926.55  1142.5 1927.17
  1220.4 1930.82  1452.4 1927.65  1512.9 1930.98  1563.3 1938.76  1754.9 2033.65
    1876 2085.38  2047.4 2170.98  2178.5 2209.84  2370.2 2279.06  2440.8 2289.48
  2481.1 2299.85  2511.4  2313.8  2571.9 2350.83    2582 2353.74  2612.2 2351.21
#Mann= 3 , 0 , 0
       0      .1       0  1093.5    .045       0  1142.5     .06       0
Bank Sta=1093.5,1142.5
XS Rating Curve= 0 ,0
Exp/Cntr=0.3,0.1

Type RM Length L Ch R = 1 ,44695.1 ,848.3,841.1,834
XS GIS Cut Line= 2
     2146901.266      367971.887     2144997.483      367559.019
#Sta/Elev= 30
       0 2366.68   100.9 2316.35   282.6 2202.33   403.7 2131.18   484.5 2089.52
     646 2002.53   746.9  1954.4   807.5 1931.66   817.6 1929.11     969 1928.33
   979.1 1927.82   997.5 1924.16  1019.4 1920.06    1047  1922.3  1069.9 1925.49
  1090.1 1926.67  1201.1 1927.38  1211.2 1928.56  1221.3 1932.51  1231.4  1939.8
  1261.7 1968.04  1281.9 1985.08  1433.3 2097.41  1503.9 2147.84  1534.2 2168.08
  1635.1 2221.13    1726 2262.04  1816.8    2309  1877.4 2343.32    1948 2390.18
#Mann= 3 , 0 , 0
       0     .08       0   997.5    .045       0    1047     .08       0
Bank Sta=997.5,1047
XS Rating Curve= 0 ,0
Exp/Cntr=0.3,0.1

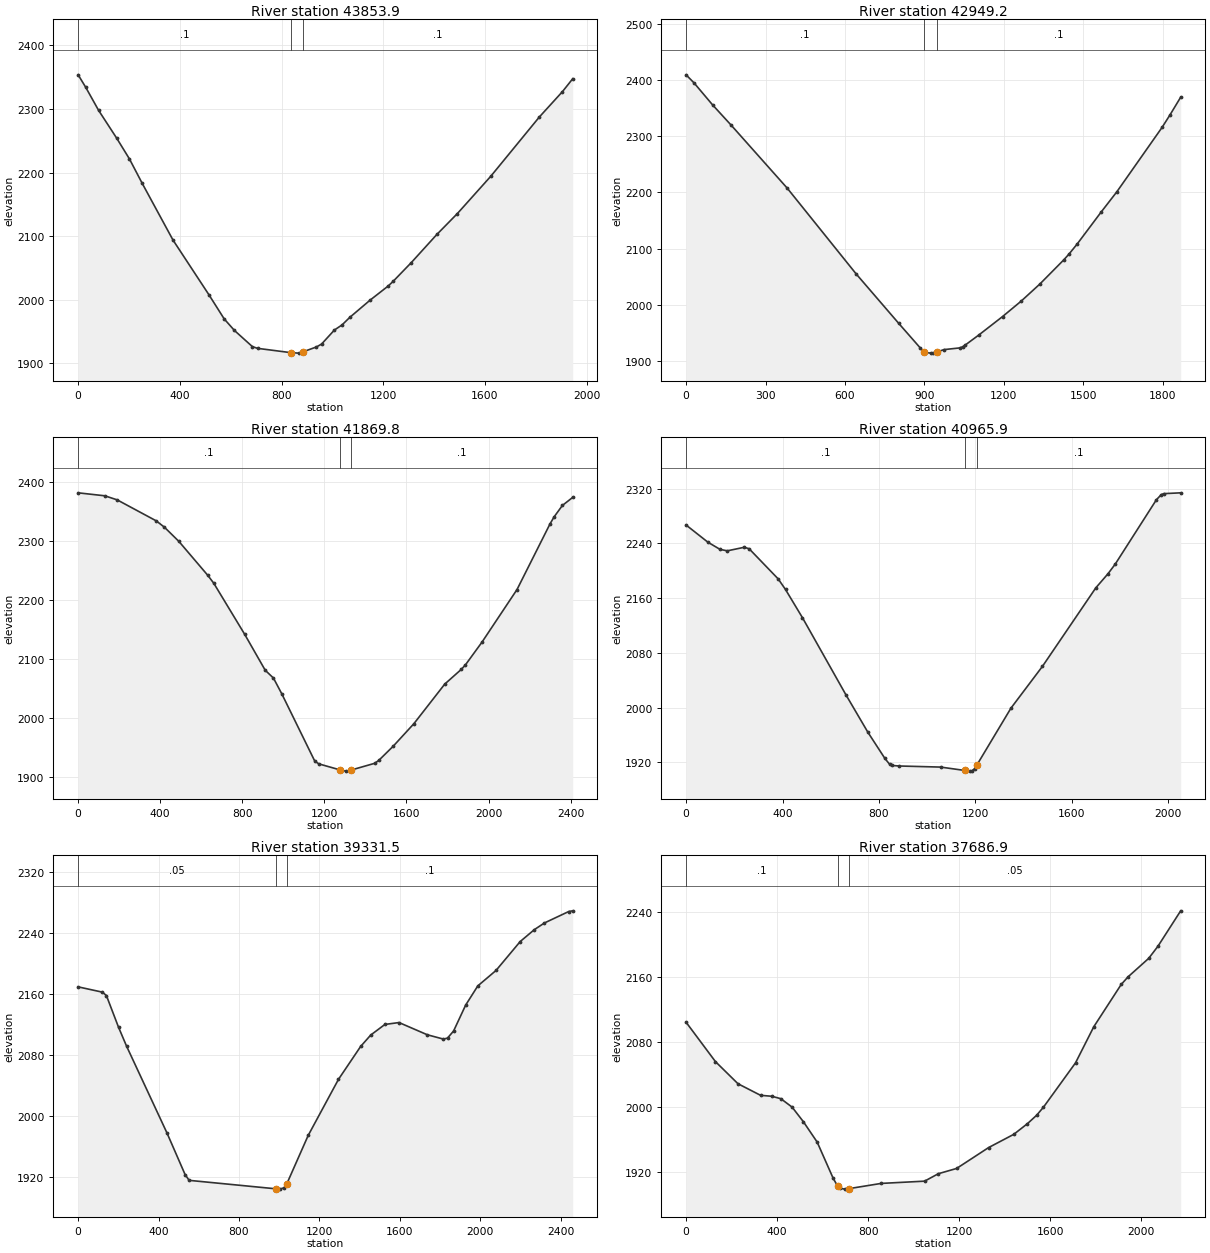
Type RM Length L Ch R = 1 ,43853.9 ,915.8,904.8,893.8
XS GIS Cut Line= 2
     2146863.037      366901.487     2144921.026      367008.527
#Sta/Elev= 30
       0 2353.65    30.2 2333.76    80.6 2297.67   151.2 2254.29   201.6 2221.53
   251.9 2183.06   372.9 2093.98     514 2008.07   574.4  1969.9   614.7 1951.76
   685.3 1926.34   705.4 1923.67   835.5 1916.94   866.7 1916.14   885.3 1918.34
   937.2 1925.86   957.4 1930.44  1007.8 1952.46    1038 1960.55  1068.2 1972.35
  1148.8 1999.68  1219.4 2021.68  1239.5  2029.3  1310.1 2058.45  1410.8 2102.76
  1491.5 2135.61  1622.5 2194.08    1814  2287.5  1904.6 2327.26    1945 2347.56
#Mann= 3 , 0 , 0
       0      .1       0   835.5    .045       0   885.3      .1       0
Bank Sta=835.5,885.3
XS Rating Curve= 0 ,0
Exp/Cntr=0.3,0.1

Type RM Length L Ch R = 1 ,42949.2 ,1076.1,1079.4,1082.7
XS GIS Cut Line= 2
     2146356.765      365832.753     2144676.363      366649.179
#Sta/Elev= 30
       0  2409.1    30.1 2394.71   100.4  2355.5   170.8 2319.35   381.7 2207.88
   642.8 2055.08   803.5 1967.26   883.9 1924.12   893.9 1918.96   898.8  1917.4
     904 1915.74   924.1 1914.56   934.1 1914.85   948.9 1916.97   974.3 1920.81
  1034.6 1923.88  1044.6 1925.87  1054.6    1929  1104.9 1946.48  1195.3 1979.51
  1265.6 2006.93  1335.9 2037.17  1426.3 2080.15  1446.4 2090.62  1476.5 2108.02
  1566.9 2164.74  1627.2 2201.35  1797.9 2315.69  1828.1  2338.1  1868.2 2369.36
#Mann= 3 , 0 , 0
       0      .1       0   898.8    .045       0   948.9      .1       0
Bank Sta=898.8,948.9
XS Rating Curve= 0 ,0
Exp/Cntr=0.3,0.1

Type RM Length L Ch R = 1 ,41869.8 ,903,903.9,904.7
XS GIS Cut Line= 3
     2146206.534      365638.704     2145436.599      365150.453
     2144021.922      365644.964
#Sta/Elev= 30
       0 2381.06   130.2 2376.01   190.4 2369.11   380.7 2333.57   420.8 2322.74
   490.9 2298.83   631.2 2241.59   661.2 2227.84   811.5 2141.55   911.7 2080.64
   951.9 2067.35   992.2 2040.88  1153.1 1926.81  1173.2 1922.08  1277.2 1911.81
    1304 1909.83  1327.7  1911.4  1444.8 1923.03  1464.9 1927.94  1535.3 1951.99
  1635.9 1990.04  1786.7 2057.24  1867.2 2082.12  1887.3 2089.71  1967.8 2128.12
  2138.8 2217.33  2299.7 2328.55  2319.8 2340.49    2360 2359.72  2410.3 2373.38
#Mann= 3 , 0 , 0
       0      .1       0  1277.2    .045       0  1327.7      .1       0
Bank Sta=1277.2,1327.7
XS Rating Curve= 0 ,0
Exp/Cntr=0.3,0.1

Type RM Length L Ch R = 1 ,40965.9 ,1635.8,1634.4,1633
XS GIS Cut Line= 2
      2145755.84      364142.652     2143802.835      364768.615
#Sta/Elev= 30
       0 2266.77    90.5 2241.68   140.8  2231.2   170.9  2229.1   241.3 2234.29
   261.4 2232.14     382 2188.05   412.2 2172.63   482.6  2131.4   663.5  2018.4
     754 1964.06   824.4 1925.91   844.5 1917.11   854.5 1915.63   884.7 1914.89
  1055.6  1913.3  1154.6 1908.42  1176.2  1907.4  1186.3 1907.96  1196.3 1911.05
  1205.4  1916.1  1347.1 1999.39  1477.8 2060.46    1699 2175.07  1749.3 2195.54
  1779.4 2209.66  1950.3 2303.74  1970.4 2311.14  1980.5 2312.59  2050.9  2313.8
#Mann= 3 , 0 , 0
       0      .1       0  1154.6    .045       0  1205.4      .1       0
Bank Sta=1154.6,1205.4
XS Rating Curve= 0 ,0
Exp/Cntr=0.3,0.1

Type RM Length L Ch R = 1 ,39331.5 ,1646.7,1644.6,1642.6
XS GIS Cut Line= 3
     2145054.761      362602.783     2143627.565      363141.111
     2142970.304      363804.632
#Sta/Elev= 30
       0 2169.36   120.4 2162.44   140.5 2158.01   200.7 2116.56   240.8 2091.69
   441.6 1978.07   531.9 1923.49   551.9 1915.95   985.2 1904.82  1003.5 1904.46
  1023.6 1906.22  1036.6 1910.83    1144 1974.84  1294.5 2048.25  1404.9  2091.4
  1455.1 2106.32  1525.4 2120.15  1595.6 2122.62  1736.2 2106.61  1816.6 2100.95
  1836.7  2102.3  1866.8 2111.53    1927 2145.53  1987.3 2170.63  2077.7 2190.81
  2198.2 2228.75  2268.5 2244.32  2318.7 2253.06  2439.2 2268.01  2459.3 2268.94
#Mann= 3 , 0 , 0
       0     .05       0   985.2    .045       0  1036.6      .1       0
Bank Sta=985.2,1036.6
XS Rating Curve= 0 ,0
Exp/Cntr=0.3,0.1

Type RM Length L Ch R = 1 ,37686.9 ,2127.3,2160.3,2193.2
XS GIS Cut Line= 3
     2144561.677      361190.139      2144059.48      361307.039
     2142557.168      362008.118
#Sta/Elev= 30
       0 2103.91   128.9 2055.54   228.1 2028.28   327.2 2014.09   376.8  2012.9
   416.5  2009.9     466 1999.52   515.6 1981.55   575.9 1956.64   646.2 1912.15
   665.6 1902.59   676.4 1899.89   696.5 1898.74   717.5 1899.42   857.2 1905.76
  1048.1 1908.54  1108.4 1917.68  1188.8 1924.16  1329.5 1949.85    1440  1966.1
  1500.3 1979.27  1540.5 1989.57  1570.6 1999.54  1711.3 2053.95  1791.7 2098.41
  1912.2 2150.39  1942.4 2159.77  2032.8 2182.41    2073 2197.12  2173.5 2240.89
#Mann= 3 , 0 , 0
       0      .1       0   665.6    .045       0   717.5     .05       0
Bank Sta=665.6,717.5
XS Rating Curve= 0 ,0
Exp/Cntr=0.3,0.1

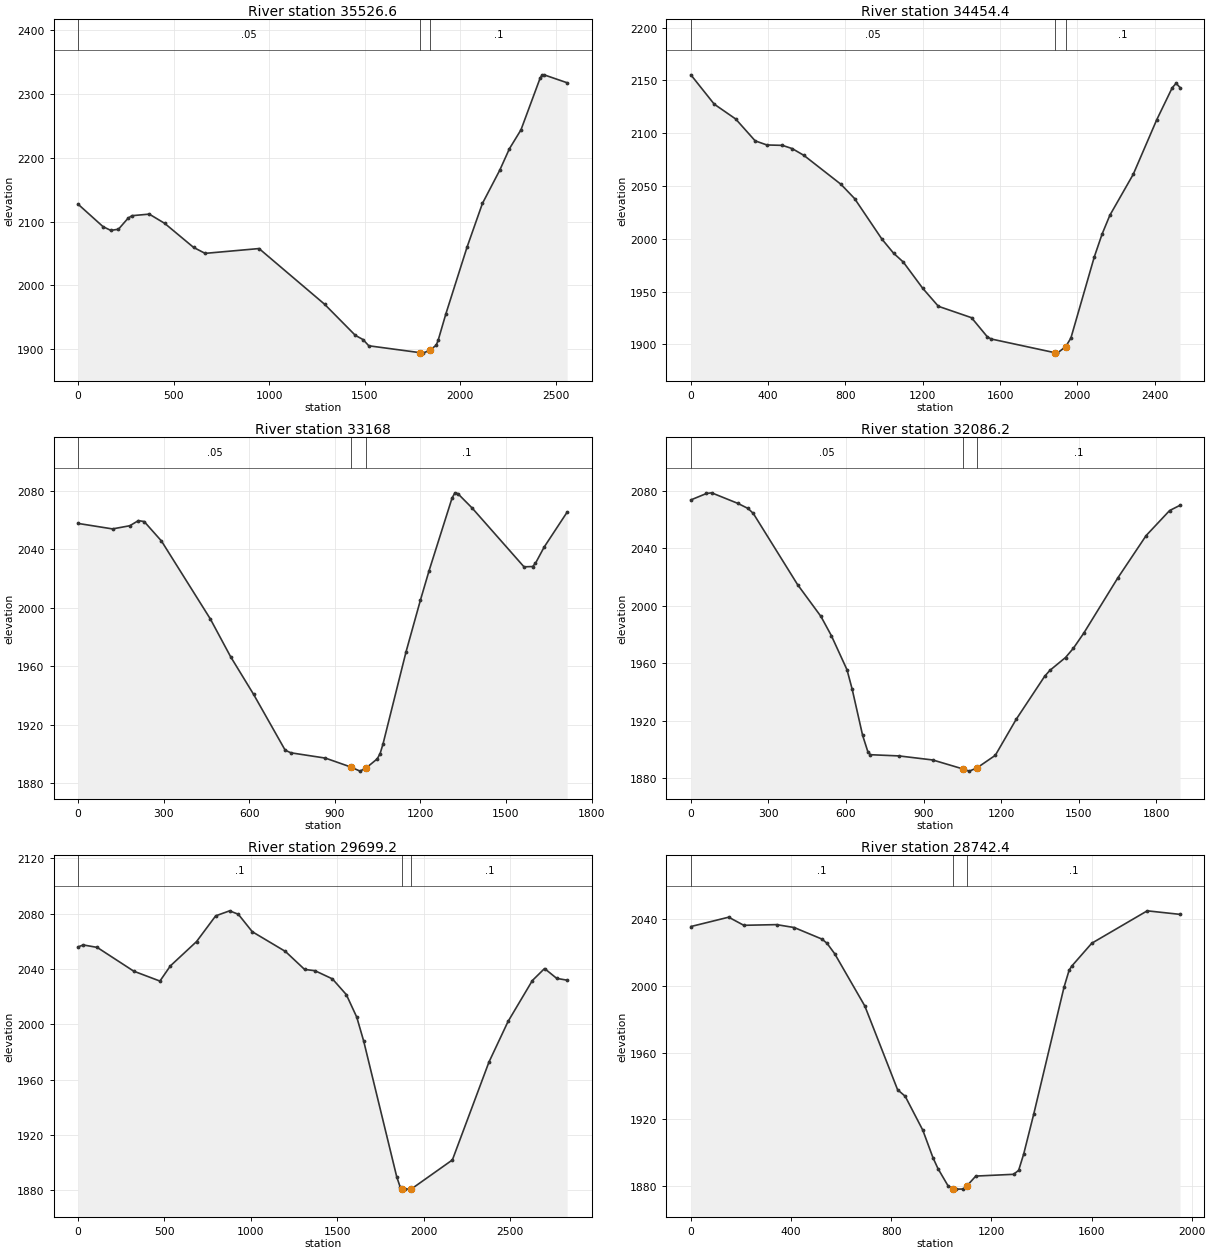
Type RM Length L Ch R = 1 ,35526.6 ,1069.2,1072.2,1075.3
XS GIS Cut Line= 2
     2144503.914      360956.499     2142657.322      359185.024
#Sta/Elev= 30
       0 2127.62     131 2092.29   171.3 2086.44   211.6 2088.22   261.9 2105.53
   282.1 2109.48   372.8 2111.94   453.4 2097.46   604.5 2059.76   664.9 2050.39
     947 2057.94  1289.5 1970.72  1450.7 1921.84    1491 1915.22  1521.2 1905.46
  1786.5 1894.77  1803.3 1893.94  1839.2 1898.14  1873.8 1906.39  1883.9    1914
  1924.2 1955.34    2035 2060.01  2115.6 2128.69  2206.3 2180.86  2256.7 2214.46
  2317.1 2244.03  2417.9 2325.58  2427.9 2330.21    2438 2330.39  2558.9 2317.93
#Mann= 3 , 0 , 0
       0     .05       0  1786.5    .045       0  1839.2      .1       0
Bank Sta=1786.5,1839.2
XS Rating Curve= 0 ,0
Exp/Cntr=0.3,0.1

Type RM Length L Ch R = 1 ,34454.4 ,1257.9,1286.4,1314.9
XS GIS Cut Line= 3
     2144697.962      360731.153     2144366.202      359472.967
     2143571.229      358534.022
#Sta/Elev= 30
       0 2155.26     121 2127.49     232 2113.46   332.9 2092.75   393.4 2088.87
   474.1 2088.49   524.5 2085.43     585 2079.02   776.7 2051.64   847.3 2038.14
   988.5 1999.82    1049 1986.43  1099.5 1978.01  1200.3 1953.11    1281 1936.16
  1452.5 1925.37  1533.1 1907.53  1553.3 1905.25  1886.7 1892.12  1896.2 1891.83
  1939.8 1897.96  1966.8 1906.14  2087.8 1982.89  2128.1  2004.5  2168.4 2022.34
  2289.4 2061.11  2410.5 2112.54  2491.1 2143.04  2511.3 2147.22  2531.5 2143.26
#Mann= 3 , 0 , 0
       0     .05       0  1886.7    .045       0  1939.8      .1       0
Bank Sta=1886.7,1939.8
XS Rating Curve= 0 ,0
Exp/Cntr=0.3,0.1

Type RM Length L Ch R = 1 ,33168   ,1090.5,1081.8,1073.1
XS GIS Cut Line= 2
     2144704.222      360080.151      2145288.02      358468.264
#Sta/Elev= 30
       0 2057.65     121  2053.9   181.5 2056.07   211.8 2059.57   231.9 2058.94
   292.4 2045.67   463.9 1992.37   534.5 1966.73   615.2 1940.96   726.1 1902.75
   746.2 1900.96   867.3 1897.34   956.7 1891.22   988.3 1888.45  1010.2 1890.68
  1048.8 1896.83  1058.9 1900.49    1069    1907  1149.6 1969.88    1200 2005.19
  1230.3 2025.28    1311 2075.02  1321.1 2078.55  1331.1 2078.03  1381.6 2068.12
  1563.1    2028  1593.3 2028.21  1603.4 2030.47  1633.7 2041.48  1714.4 2065.39
#Mann= 3 , 0 , 0
       0     .05       0   956.7    .045       0  1010.2      .1       0
Bank Sta=956.7,1010.2
XS Rating Curve= 0 ,0
Exp/Cntr=0.3,0.1

Type RM Length L Ch R = 1 ,32086.2 ,2428.4,2387,2345.5
XS GIS Cut Line= 2
     2146050.043      360474.508     2146098.466       358582.95
#Sta/Elev= 30
       0 2073.71    60.4 2078.18    80.5 2078.64   181.2 2071.34   221.4 2067.75
   241.6 2064.28   412.7 2014.81   503.2 1992.65   543.5 1979.29   603.9  1955.6
     624 1942.05   664.3 1910.01   684.4 1898.68   694.5 1896.46   805.2 1895.62
     936 1892.79  1052.4 1886.56  1076.9 1885.04  1106.3 1887.23  1177.6 1896.02
  1258.1 1920.99  1368.8 1951.07  1388.9 1955.15  1449.3 1964.08  1479.5 1970.47
  1519.8 1981.01  1650.6 2019.19  1761.3 2048.95  1851.9 2066.31  1892.2 2069.96
#Mann= 3 , 0 , 0
       0     .05       0  1052.4    .045       0  1106.3      .1       0
Bank Sta=1052.4,1106.3
XS Rating Curve= 0 ,0
Exp/Cntr=0.3,0.1

Type RM Length L Ch R = 1 ,29699.2 ,957.8,956.8,955.7
XS GIS Cut Line= 3
     2148441.222      359466.707     2148053.125      358214.781
     2146534.271      358185.373
#Sta/Elev= 30
       0 2055.94    30.2 2057.39   110.9 2055.62   322.6 2038.42   473.9 2031.27
   534.4 2042.24   685.6  2059.8   796.5 2078.42   877.2 2082.05   927.6 2079.54
  1008.2 2066.95  1199.8 2052.69  1310.7  2039.7  1371.1 2038.75  1471.7 2032.86
  1552.2 2021.49  1612.5 2005.22  1652.8 1987.82  1843.9 1889.74    1864 1882.29
  1873.8 1881.08  1894.2 1880.87  1928.5 1880.97  2165.8 1901.97  2377.1 1972.65
  2487.8 2002.07  2628.6 2031.68    2699 2040.34  2769.5  2033.2  2829.8 2031.91
#Mann= 3 , 0 , 0
       0      .1       0  1873.8    .045       0  1928.5      .1       0
Bank Sta=1873.8,1928.5
XS Rating Curve= 0 ,0
Exp/Cntr=0.3,0.1

Type RM Length L Ch R = 1 ,28742.4 ,1447.7,1429.5,1407.5
XS GIS Cut Line= 2
     2148497.559      357232.018     2146544.554      357269.576
#Sta/Elev= 30
       0 2035.41     151    2041   211.4 2036.15   342.3 2036.55   412.8 2034.81
   523.6 2027.89   543.7 2025.39   573.9 2019.25   694.8 1987.83   825.6 1937.74
   855.9 1933.84   926.3 1913.52   966.6 1897.17   986.8 1890.56    1027 1880.26
  1046.6 1878.34  1057.2 1878.27  1087.4 1878.33  1101.7 1880.11  1137.8 1886.08
  1288.8 1887.14    1309 1889.53  1329.1 1899.28  1369.4 1923.29  1490.2 1999.14
  1510.3 2009.14  1520.4 2011.63    1601 2025.42  1822.5 2044.81  1953.4 2042.69
#Mann= 3 , 0 , 0
       0      .1       0  1046.6    .045       0  1101.7      .1       0
Bank Sta=1046.6,1101.7
XS Rating Curve= 0 ,0
Exp/Cntr=0.3,0.1

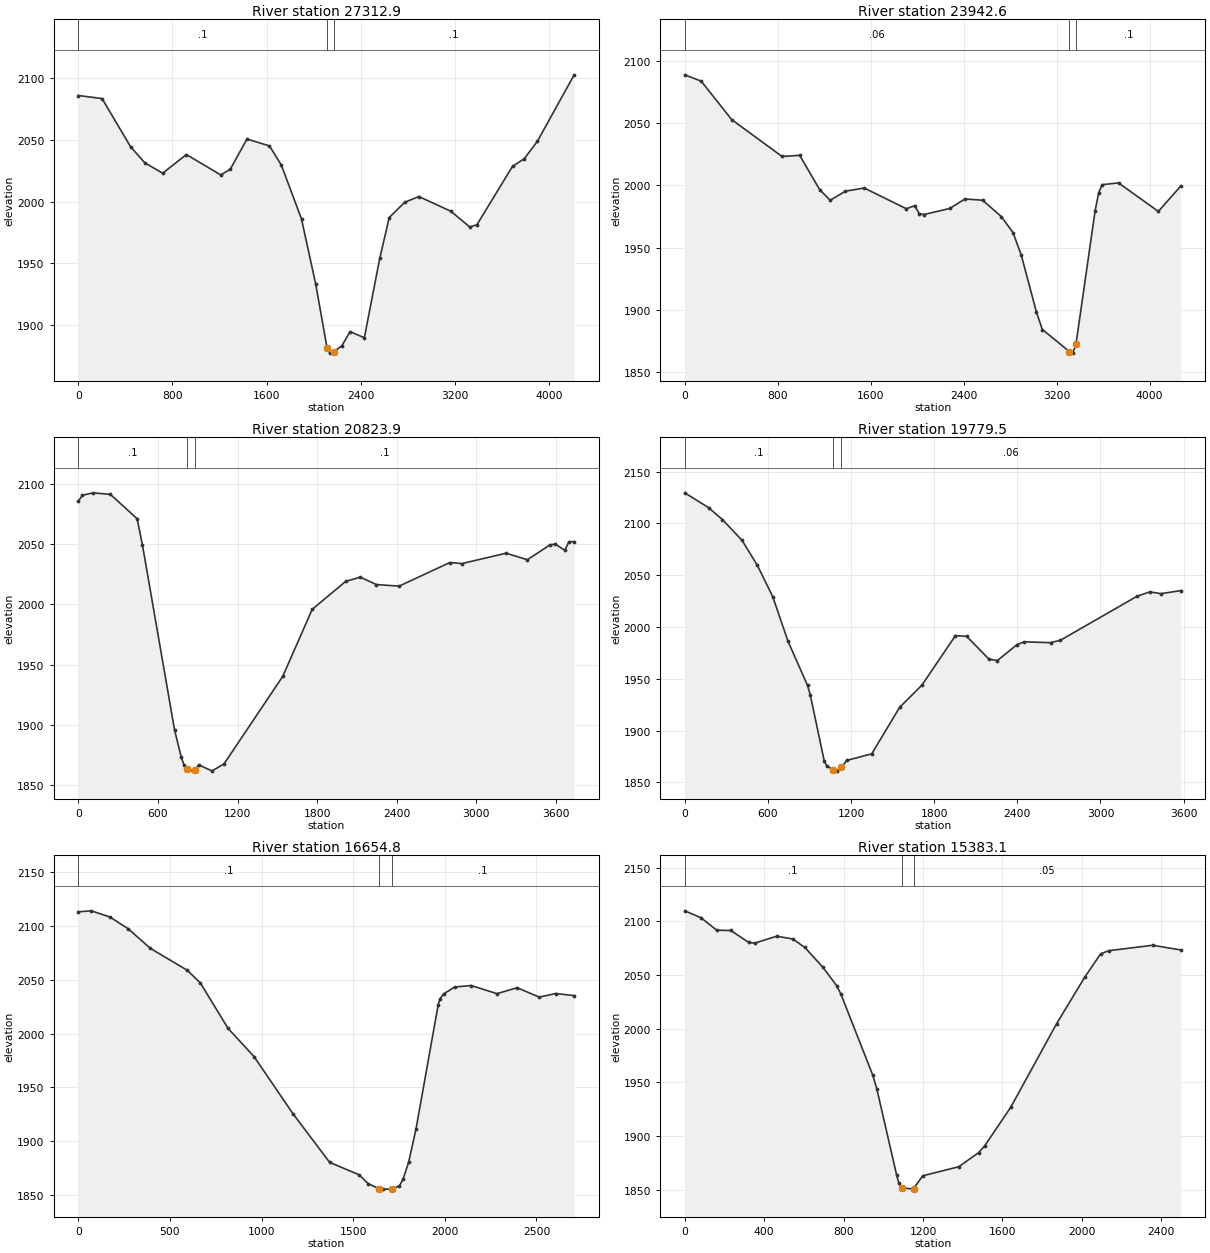
Type RM Length L Ch R = 1 ,27312.9 ,3336.2,3370.3,3404.4
XS GIS Cut Line= 3
      2149161.08      356099.025     2147527.316      355729.707
     2145436.599      357169.422
#Sta/Elev= 30
       0 2086.09   201.8  2083.6     444 2044.55   565.1 2031.52   716.4  2023.1
   918.2  2038.2  1210.8 2021.72  1291.6 2026.36  1432.8 2050.84  1624.5 2045.22
  1725.4 2029.66  1896.6 1985.95  2017.5 1933.12  2114.4 1881.05  2138.4 1877.27
  2169.9 1878.36  2239.1 1883.19  2309.6 1894.68  2430.5 1889.72  2561.4 1954.06
    2642 1987.16    2773  1999.5  2893.9 2004.18  3165.8 1992.27    3327 1979.49
  3387.4 1981.39  3689.6 2028.64  3790.4 2034.92  3901.2 2049.02  4213.5 2102.85
#Mann= 3 , 0 , 0
       0      .1       0  2114.4    .045       0  2169.9      .1       0
Bank Sta=2114.4,2169.9
XS Rating Curve= 0 ,0
Exp/Cntr=0.3,0.1

Type RM Length L Ch R = 1 ,23942.6 ,3116.7,3118.7,3119.4
XS GIS Cut Line= 3
     2149136.042      355967.573      2146431.88      355222.676
      2145242.55      354371.366
#Sta/Elev= 30
       0 2088.78   141.2 2083.72   403.6 2052.83   837.4 2023.21   988.8 2024.15
  1160.3 1996.66  1251.1 1988.02  1382.3 1995.35  1543.7 1997.91  1906.9 1981.26
  1977.5 1983.65  2017.9  1977.4  2058.3 1976.62  2280.2 1981.47  2411.4 1989.11
  2562.7  1988.1  2724.2    1975    2825 1962.08  2895.7 1944.15  3026.8 1898.17
  3077.2  1884.3    3310 1866.63  3339.5 1865.33  3366.7 1872.49  3531.1 1979.32
  3561.4 1993.83  3591.7 2000.58  3732.9    2002  4075.8 1979.09  4267.5 1999.36
#Mann= 3 , 0 , 0
       0     .06       0    3310    .045       0  3366.7      .1       0
Bank Sta=3310,3366.7
XS Rating Curve= 0 ,0
Exp/Cntr=0.3,0.1

Type RM Length L Ch R = 1 ,20823.9 ,1052.5,1044.4,1039
XS GIS Cut Line= 2
     2149248.715      355742.226     2146300.428      353444.941
#Sta/Elev= 30
       0 2085.54    30.2 2090.48   110.8 2092.53   241.8 2091.23   443.3 2071.08
   483.6  2049.1   725.4 1895.99   775.7  1873.5   795.9 1867.28   820.8 1864.03
   866.4 1861.88   878.6 1862.41   906.7 1867.07  1007.4 1862.03  1098.1 1867.84
  1541.4 1940.52    1763 1995.97  2014.9 2019.08  2125.7 2022.64  2246.6 2016.52
  2417.9 2015.19  2800.7 2034.78  2891.4  2033.9  3223.8 2042.48    3385 2037.08
  3556.3 2049.47  3596.6 2049.98  3667.1 2044.84  3697.3 2051.89  3737.6 2052.15
#Mann= 3 , 0 , 0
       0      .1       0   820.8    .045       0   878.6      .1       0
Bank Sta=820.8,878.6
XS Rating Curve= 0 ,0
Exp/Cntr=0.3,0.1

Type RM Length L Ch R = 1 ,19779.5 ,3123.1,3124.7,3124.4
XS GIS Cut Line= 3
     2149824.601      354246.174     2147871.596      354271.212
     2146532.035      353351.046
#Sta/Elev= 30
       0 2129.63   171.2 2115.32   271.8 2103.78   412.8 2083.78   523.5 2059.62
   634.3 2029.43     745 1986.15     886 1943.48   906.1 1934.08  1006.8 1870.24
  1026.9 1865.41  1072.6 1862.08  1097.4 1860.75  1130.8 1864.42  1167.9 1871.08
  1349.1 1877.48  1550.4 1922.33  1711.5 1943.88  1953.2 1991.68  2033.9    1991
  2195.4 1968.94    2256  1967.6  2397.3 1982.94  2447.8 1985.68  2639.6 1984.87
  2710.2 1987.16  3265.4 2029.82  3356.2 2033.93    3437  2032.2  3578.3 2035.16
#Mann= 3 , 0 , 0
       0      .1       0  1072.6    .045       0  1130.8     .06       0
Bank Sta=1072.6,1130.8
XS Rating Curve= 0 ,0
Exp/Cntr=0.3,0.1

Type RM Length L Ch R = 1 ,16654.8 ,1273.2,1271.8,1270.1
XS GIS Cut Line= 3
     2149123.522       352944.17     2147946.711      353038.065
      2146733.06      352114.676
#Sta/Elev= 30
       0 2113.06    70.6 2113.94   171.5 2108.27   272.4 2097.27   393.5 2079.04
   595.3 2058.68     666 2046.93   817.3 2004.78   958.6 1978.74  1170.5 1925.83
  1371.2 1880.51  1531.7 1868.99  1581.9 1860.74  1638.3 1856.22  1662.1 1855.67
  1712.3 1855.67  1752.4 1858.74  1772.5 1865.17  1802.6 1880.81  1842.7 1911.63
  1963.1  2026.2  1973.1 2032.18  1993.2 2036.79  2053.4 2043.24  2143.7 2044.62
  2284.2 2037.08  2394.5 2042.58  2514.9 2033.87  2605.2 2037.19  2705.5 2035.26
#Mann= 3 , 0 , 0
       0      .1       0  1638.3    .045       0  1712.3      .1       0
Bank Sta=1638.3,1712.3
XS Rating Curve= 0 ,0
Exp/Cntr=0.3,0.1

Type RM Length L Ch R = 1 ,15383.1 ,1917.2,1943.6,1970
XS GIS Cut Line= 2
     2149474.062      352643.708     2147314.134      351388.333
#Sta/Elev= 30
       0 2109.78    80.6 2103.44   161.2 2091.74   231.7 2091.47   322.4 2080.32
   352.6 2079.76   463.4 2086.16     544 2083.55   604.4 2075.78   695.1 2057.42
   765.6 2040.01   785.7 2032.65   946.9 1956.92   967.1 1944.37  1067.8 1863.46
  1077.9 1856.55  1092.8 1852.11  1148.4 1850.72  1152.4  1851.1  1198.8 1863.13
  1380.1 1871.56  1480.8 1884.72    1511 1891.03    1642 1926.87  1873.7 2004.84
  2014.7 2047.91  2095.3 2069.74  2135.6 2072.66  2357.2 2077.72  2498.2 2073.39
#Mann= 3 , 0 , 0
       0      .1       0  1092.8    .045       0  1152.4     .05       0
Bank Sta=1092.8,1152.4
XS Rating Curve= 0 ,0
Exp/Cntr=0.3,0.1