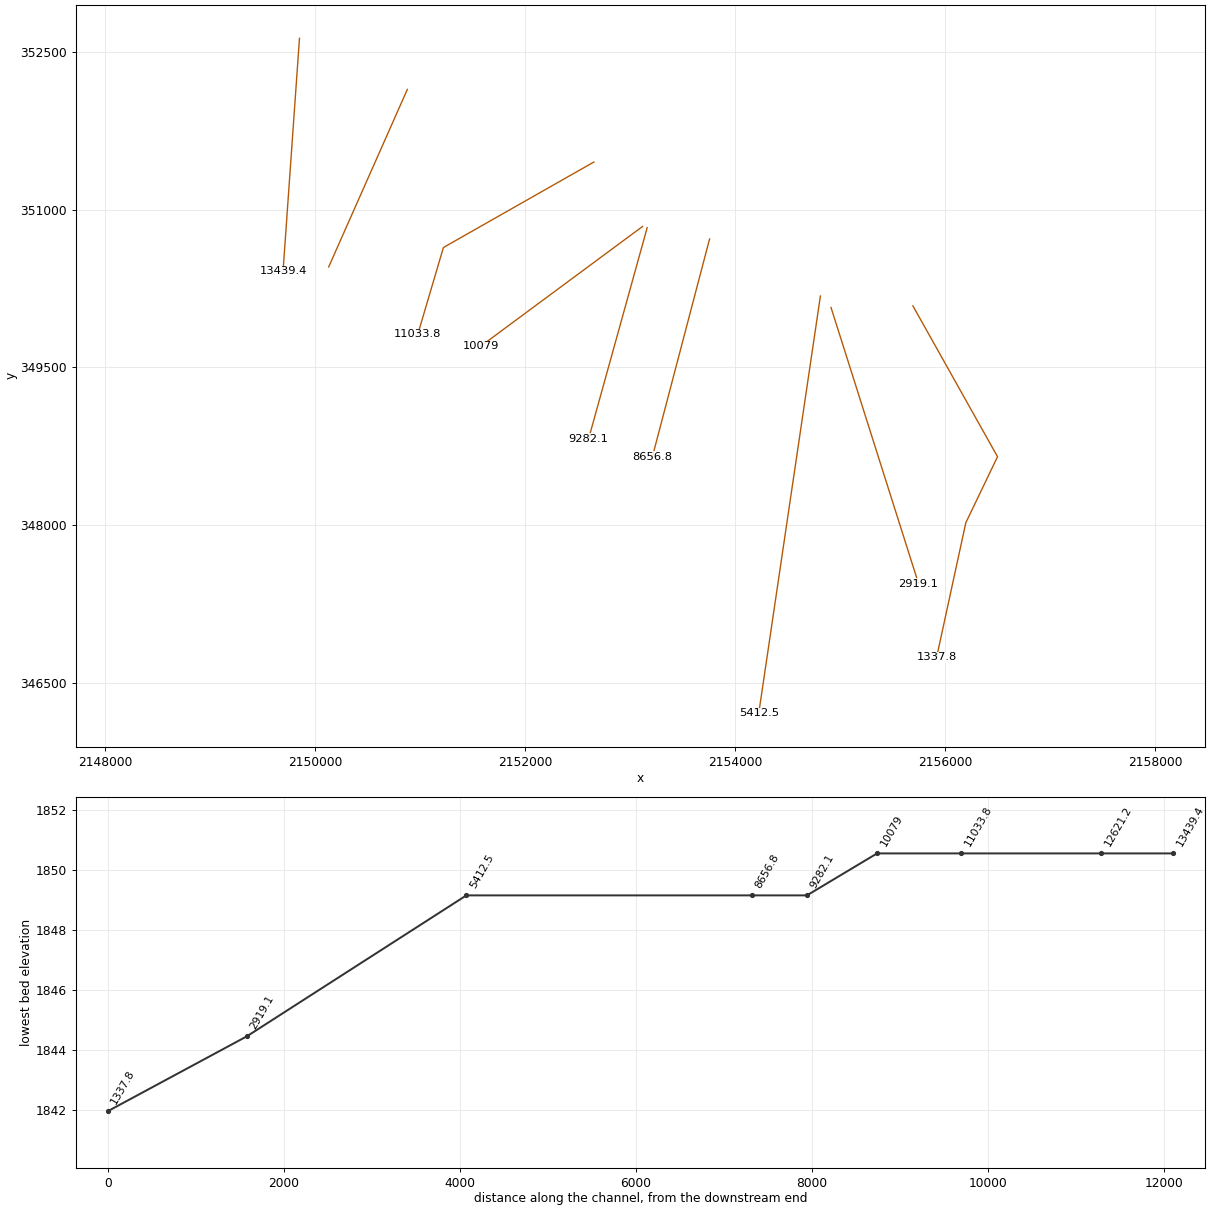
HEC-RAS study SpringCk.prj: SpringCk

--- SpringCk.g01 (geometry) --- (continued)

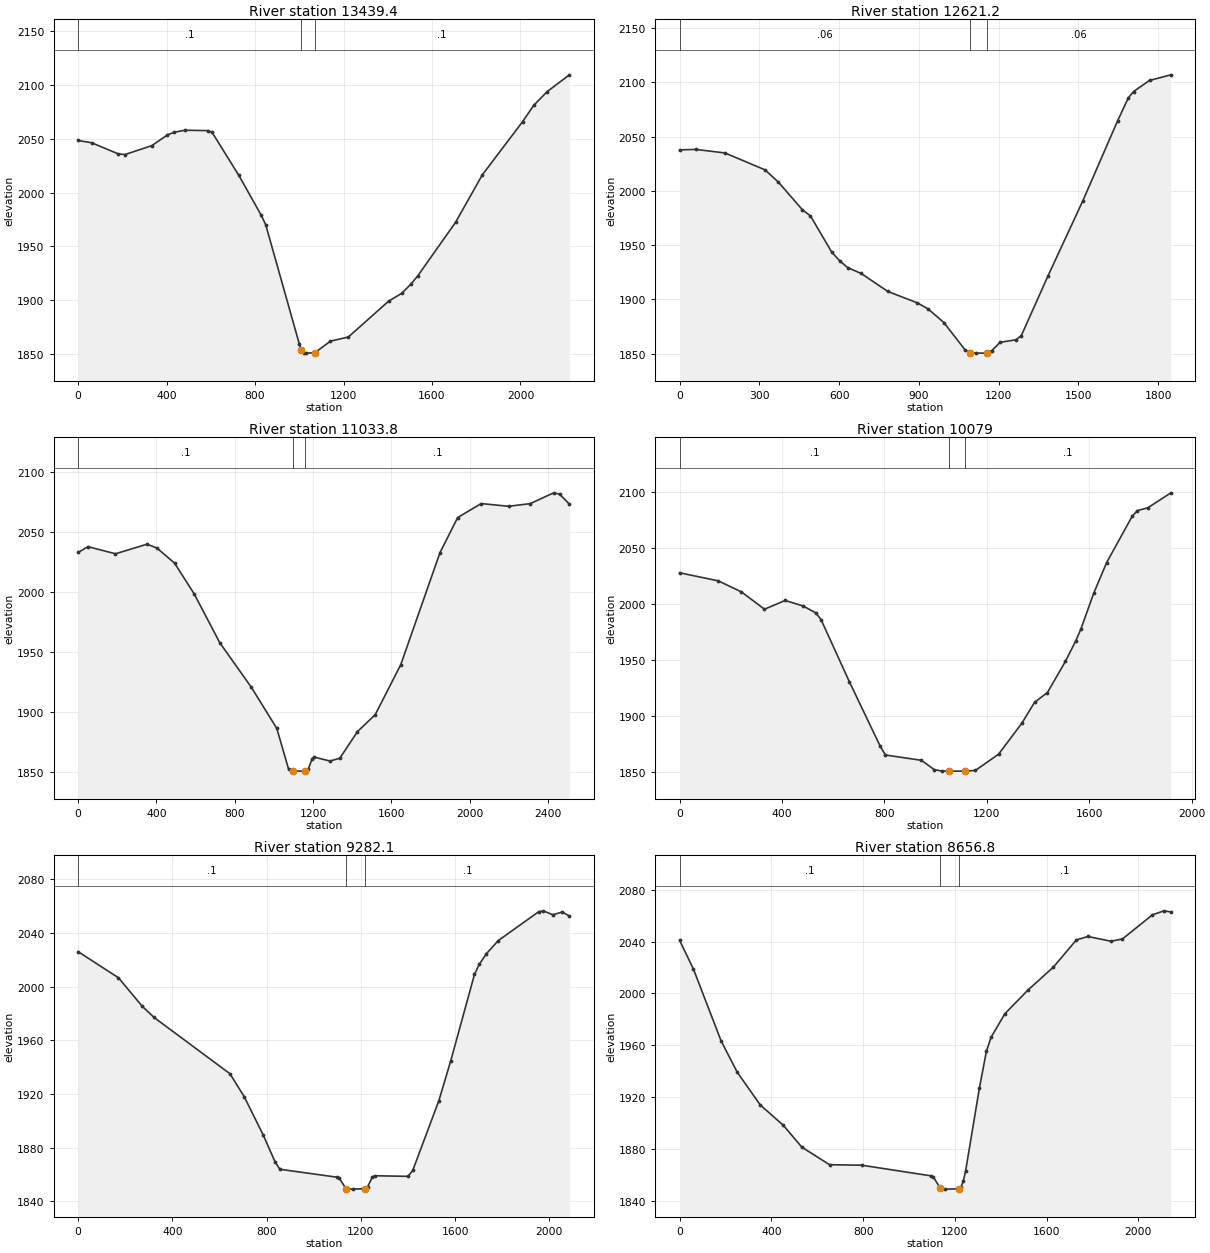
Type RM Length L Ch R = 1 ,13439.4 ,827.3,818.3,809.3
XS GIS Cut Line= 2
      2149849.64      352631.189     2149693.149      350415.279
#Sta/Elev= 30
       0 2048.49    60.6 2046.43   181.8 2036.02     212 2035.42   333.2  2043.7
   403.9 2053.66   434.2 2056.17   484.7 2058.07   585.6 2057.67   605.8 2056.07
     727 2015.92     828 1978.89   848.2 1970.13   999.6 1859.49  1009.7 1853.54
  1019.8 1850.97  1029.9 1850.56  1070.3 1850.89    1141 1861.72  1221.8 1865.55
  1403.5 1898.87  1464.1 1906.34  1504.5 1914.81  1534.8  1922.2  1706.5 1972.27
  1827.6 2016.51  2009.4 2065.95  2059.9 2081.18  2120.4 2093.91  2221.4 2109.62
#Mann= 3 , 0 , 0
       0      .1       0  1009.7    .045       0  1070.3      .1       0
Bank Sta=1009.7,1070.3
XS Rating Curve= 0 ,0
Exp/Cntr=0.3,0.1

Type RM Length L Ch R = 1 ,12621.2 ,1604.6,1587.4,1570.2
XS GIS Cut Line= 2
     2150877.037      352145.259     2150127.757      350455.556
#Sta/Elev= 30
       0 2037.84    60.3 2038.29   170.8 2035.02   321.5 2019.42   371.7 2008.14
   462.1 1982.63   492.2 1977.05   572.6 1943.56   602.7 1935.51   632.9 1929.29
   683.1 1923.98   783.6 1907.36     894 1896.93   934.2 1891.42   994.5 1878.68
  1074.9 1853.29  1094.4 1850.71  1115.1 1850.56    1155  1850.6  1175.3 1852.98
  1205.5 1860.53  1265.7 1862.87  1285.8  1866.8  1386.3 1921.91  1516.9 1990.85
  1647.5  2064.4  1687.6  2085.5  1707.7 2091.62    1768 2101.83  1848.4 2107.02
#Mann= 3 , 0 , 0
       0     .06       0  1094.4    .045       0    1155     .06       0
Bank Sta=1094.4,1155
XS Rating Curve= 0 ,0
Exp/Cntr=0.3,0.1

Type RM Length L Ch R = 1 ,11033.8 ,951.6,954.8,957.9
XS GIS Cut Line= 3
     2152653.955      351454.378     2151220.499      350640.626
     2150976.373      349814.354
#Sta/Elev= 30
       0 2033.18    50.2 2038.06     191  2032.1   351.8 2040.09     402 2036.98
   492.5 2024.36     593  1998.6   723.7 1957.83   884.5 1920.71  1015.1 1886.23
  1075.4 1852.08  1095.5 1850.56  1098.6 1850.56  1159.8 1850.58  1175.9 1852.26
    1196 1861.05  1206.1  1862.3  1286.5 1858.99  1336.8 1861.29  1427.2 1883.57
  1517.7 1897.68  1648.3 1939.46  1848.7 2033.04  1938.9 2062.33  2059.1 2074.04
  2199.3 2071.76  2309.5 2073.99  2429.8 2083.01  2459.8 2081.87  2509.9 2073.55
#Mann= 3 , 0 , 0
       0      .1       0  1098.6    .045       0  1159.8      .1       0
Bank Sta=1098.6,1159.8
XS Rating Curve= 0 ,0
Exp/Cntr=0.3,0.1

Type RM Length L Ch R = 1 ,10079   ,779.4,796.9,814.4
XS GIS Cut Line= 2
     2153117.168      350840.934      2151574.29      349700.363
#Sta/Elev= 30
       0  2027.6   150.7 2020.42   241.1  2010.6   331.5 1995.08   411.9 2002.88
   482.2 1998.02   532.4 1991.71   552.5 1985.77     663 1930.37   783.6 1872.72
   803.6 1864.98   944.3 1860.22   994.5 1851.93  1024.6 1850.56  1053.6 1850.56
  1115.2 1850.56  1155.2 1851.19  1245.6 1865.66    1336 1893.13  1386.3 1911.98
  1436.5 1920.71  1506.8 1948.53    1547 1966.74  1567.1 1977.33  1617.3 2009.35
  1667.6 2036.68    1768 2078.26  1788.1 2083.13  1828.3 2085.58  1918.7 2098.97
#Mann= 3 , 0 , 0
       0      .1       0  1053.6    .045       0  1115.2      .1       0
Bank Sta=1053.6,1115.2
XS Rating Curve= 0 ,0
Exp/Cntr=0.3,0.1

Type RM Length L Ch R = 1 ,9282.1  ,625,625.3,625.6
XS GIS Cut Line= 2
     2153161.254        350829.3     2152603.236      348819.791
#Sta/Elev= 30
       0    2026   171.3 2006.56     272 1985.38   322.4 1977.01   644.8 1935.06
   705.3 1917.96   785.9 1889.43   836.2  1869.4   856.4 1863.95  1098.2 1858.07
  1108.3 1857.34  1138.5 1849.17  1168.7 1849.16  1219.1 1849.51  1229.2 1851.01
  1249.3 1858.19  1259.4 1859.12  1400.4 1858.68  1420.6  1863.1  1531.4 1915.03
  1581.8 1944.68  1682.5 2009.03  1702.7 2016.51  1732.9 2024.38  1783.3 2034.21
  1954.6 2055.67  1974.7 2056.41    2015 2053.47  2055.3 2055.52  2085.6 2052.54
#Mann= 3 , 0 , 0
       0      .1       0  1138.5    .045       0  1219.1      .1       0
Bank Sta=1138.5,1219.1
XS Rating Curve= 0 ,0
Exp/Cntr=0.3,0.1

Type RM Length L Ch R = 1 ,8656.8  ,3241.8,3244.3,3246.8
XS GIS Cut Line= 2
      2153755.65      350722.001     2153211.062      348650.063
#Sta/Elev= 30
       0 2040.99    60.4 2018.76     181 1963.44   251.4 1939.27     352 1914.01
   452.6 1898.33   533.1 1881.49   653.8    1868   794.6  1867.6  1096.3 1859.39
  1106.4 1858.56  1136.5 1849.93  1156.6 1849.16    1217 1849.41    1227 1850.88
  1237.1 1855.35  1247.2 1863.26  1307.5 1927.31  1337.7 1955.32  1357.8 1966.13
  1418.2 1984.34  1518.7 2002.57  1629.4 2020.22  1729.9 2041.24  1780.2 2043.93
  1880.8 2040.28  1931.1 2042.04  2061.8 2060.62  2112.1 2063.71  2142.3 2062.83
#Mann= 3 , 0 , 0
       0      .1       0  1136.5    .045       0    1217      .1       0
Bank Sta=1136.5,1217
XS Rating Curve= 0 ,0
Exp/Cntr=0.3,0.1

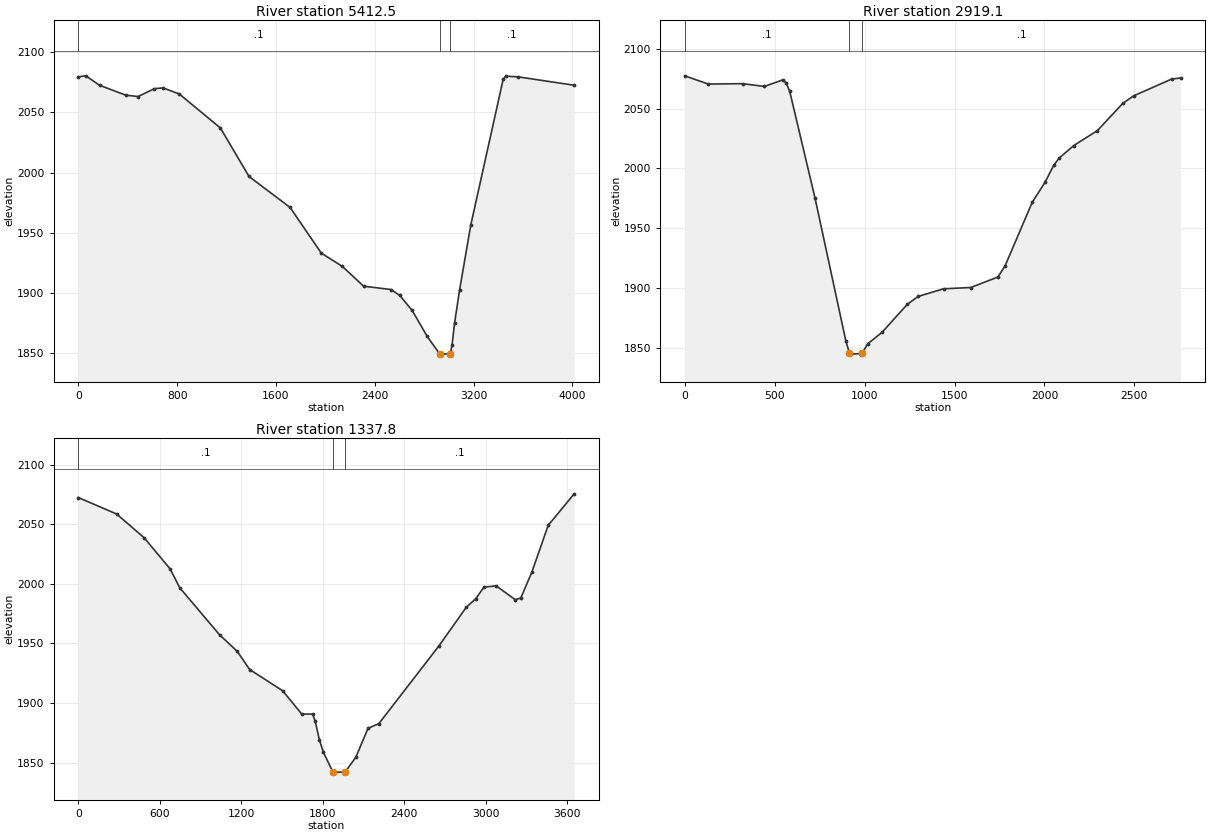
Type RM Length L Ch R = 1 ,5412.5  ,2481.3,2493.4,2505.5
XS GIS Cut Line= 2
     2154811.094      350179.152     2154223.731      346207.415
#Sta/Elev= 30
       0 2079.54    60.5 2080.39   171.5 2072.57   383.3 2064.35   484.2 2063.19
   615.4 2069.72     686 2070.34   817.1 2065.33    1150 2037.11    1382  1996.8
  1714.9    1971  1967.1 1933.14  2138.6 1921.99  2310.1 1905.61    2532 1902.82
  2602.6 1897.94  2703.5 1885.42  2824.6 1863.94  2925.4 1849.43  2945.6 1849.16
  3006.2 1849.48  3016.2 1851.29  3026.3 1856.93  3046.5 1874.93  3086.9 1902.29
  3177.6 1956.33  3439.9 2077.41  3460.1  2080.1    3561 2079.53  4014.9 2072.58
#Mann= 3 , 0 , 0
       0      .1       0  2925.4    .045       0  3006.2      .1       0
Bank Sta=2925.4,3006.2
XS Rating Curve= 0 ,0
Exp/Cntr=0.3,0.1

Type RM Length L Ch R = 1 ,2919.1  ,1600.9,1581.3,1561.7
XS GIS Cut Line= 2
     2154912.291      350069.608     2155745.865      347441.606
#Sta/Elev= 30
       0 2077.61   130.8  2070.7     322 2071.05   442.7 2068.71   543.4 2074.16
   563.5 2071.82   583.6 2064.49   724.5 1974.94   895.5 1855.49   915.7 1845.35
   925.7 1844.46   986.1 1845.04  1016.3    1853  1096.8 1862.72  1237.6 1886.25
    1298 1892.82  1438.9 1899.19  1589.8 1900.27  1740.8 1909.04    1781 1918.45
  1931.9 1971.68  2002.4 1988.27  2052.7    2003  2082.9  2008.9  2163.4 2019.23
  2294.2 2031.73    2435 2054.46  2495.4 2060.81  2706.7 2074.89    2757 2075.82
#Mann= 3 , 0 , 0
       0      .1       0   915.7    .045       0   986.1      .1       0
Bank Sta=915.7,986.1
XS Rating Curve= 0 ,0
Exp/Cntr=0.3,0.1

Type RM Length L Ch R = 1 ,1337.8  ,1347.1,1337.8,1328.6
XS GIS Cut Line= 4
     2155692.296      350084.985     2156498.105      348649.981
     2156196.104      348021.452     2155918.175      346741.968
#Sta/Elev= 30
       0 2072.45   282.7 2058.61   484.6 2038.73   676.5 2012.52   747.2 1996.73
    1040 1957.28  1171.2 1943.28  1262.1 1928.08  1504.4 1910.34  1645.8 1890.71
  1725.5  1890.7  1745.4 1884.52  1775.3 1869.23  1805.2 1858.62  1874.9 1842.14
  1884.8 1841.96  1964.6 1841.96  2044.2 1854.48  2133.9 1878.72  2213.6 1882.65
  2655.3 1947.76  2856.8  1980.2  2927.2 1987.55  2987.7 1997.23  3078.3 1998.32
  3219.3 1986.64  3259.6 1988.22  3340.2 2009.68    3461 2049.09  3652.4 2075.58
#Mann= 3 , 0 , 0
       0      .1       0  1874.9    .045       0  1964.6      .1       0
Bank Sta=1874.9,1964.6
XS Rating Curve= 0 ,0
Exp/Cntr=0.3,0.1
Stream Node=SpringCk        ,Main            , 0 , 0 ,Upstream end
Stream Node=SpringCk        ,Main            , 0 , 1 ,Downstream end

Chan Stop Cuts=-1
Use User Specified Reach Order=0